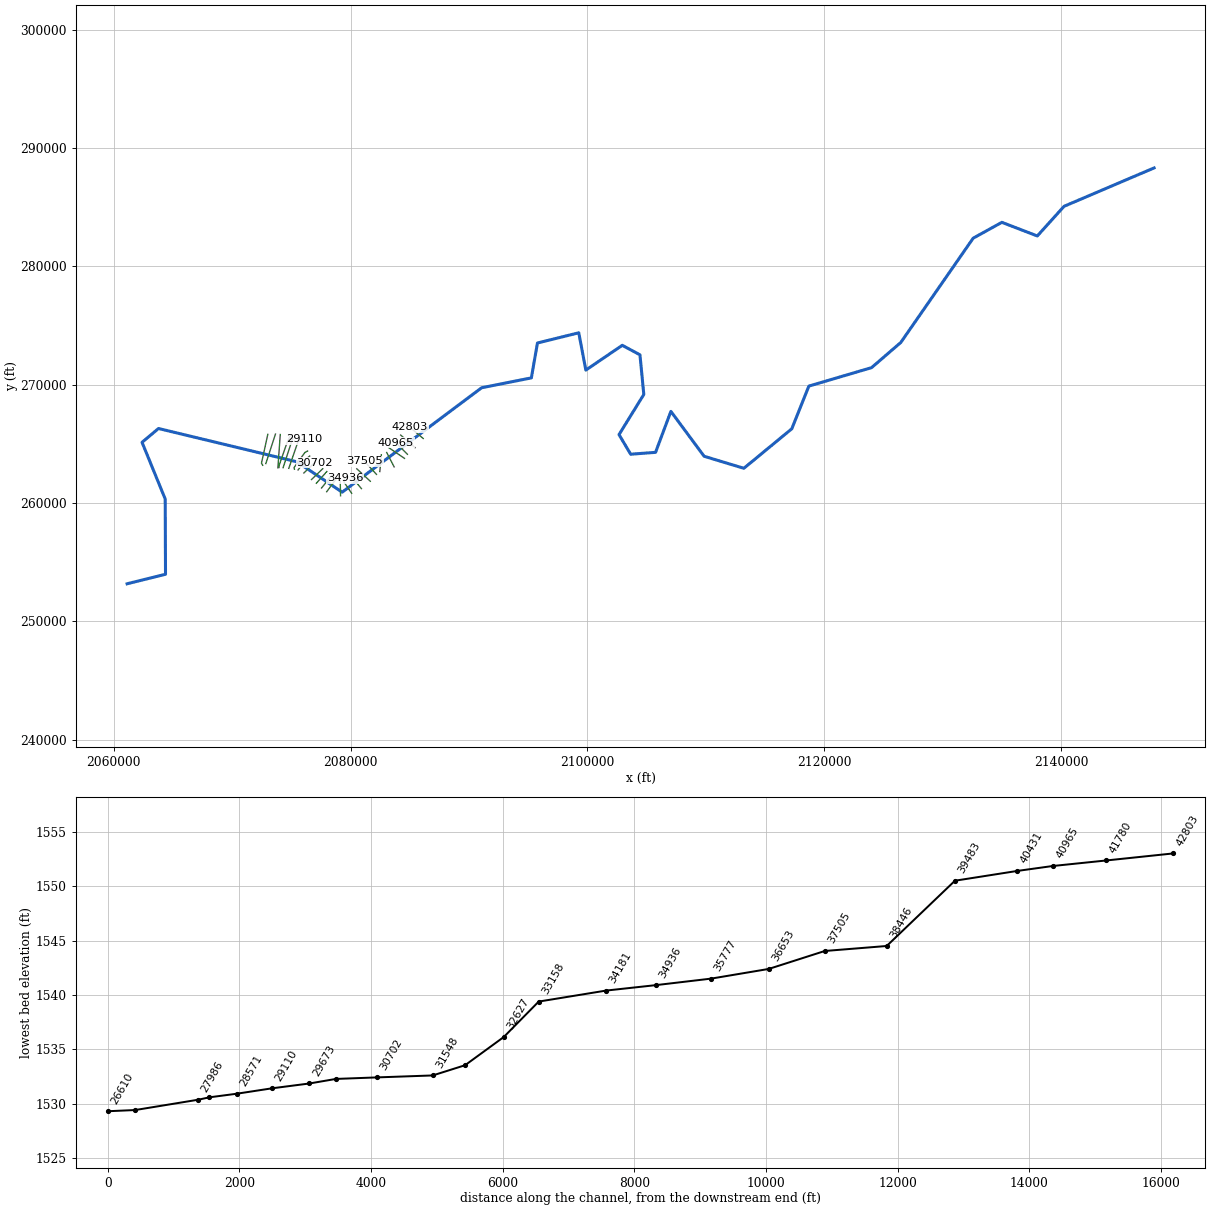
--- GREENBRRV1.prj (project) ---

Proj Title=GREENBRRV1
Current Plan=p02
Default Exp/Contr=0,0
English Units
Geom File=g01
Flow File=f01
Flow File=f02
Flow File=f03
Plan File=p01
Plan File=p02
Plan File=p03
Background Map Layer=FWY_proj
Background Map Layer=BOsSummers_Proj
Background Map Layer=HMWs
BEGIN DESCRIPTION:
Greenbrier River
Greenbrier County, WV
WV Disaster Studies / PMR
WVDHSEM-2017-2, Flood Risk Project
HEC-RAS Version: 5.0.7
Study Limits:
Upstream Extents: (3.2 mi. upstream of S Monroe St)
Downstream Extents: (0.6 mi.  Upstream of Route 3 (Howell St)); RAS model extended further downstream into Summers County to achieve a stable tie-in
General Notes: Recurrence interval flows taken from Qs values at gage at Alderson (closest flow location as defined in FIS). A downstream flow point was added by using the in between of a gage equation mentioned in the 2010 WV SIR report. Additional flow point (DA = 1500 sq.mi.) is computed using the in-between gage equations just upstream of confluence with Wolf Creek and applied conservatively at Cross section 18976 (downstream of confluence of Muddy Creek)
Boundary Conditions- Normal depth boundary conditions with slope of 0.00185 used for all plans.
END DESCRIPTION:
DSS Export Rating Curves= 0
DSS Export Rating Curve Sorted= 0
DSS Export Volume Flow Curves= 0
DXF OffsetX= 0
DXF OffsetY= 0
DXF ScaleX= 0
DXF ScaleY= 0

--- GREENBRRV1.p02 (plan) ---

Plan Title=Multiple Profiles
Program Version=5.03
Short Identifier=MultP
Geom File=g01
Flow File=f03
Subcritical Flow
K Sum by GR= 0
Std Step Tol= 0.01
Critical Tol= 0.01
Num of Std Step Trials= 20
Max Error Tol= 0.3
Flow Tol Ratio= 0.001
Split Flow NTrial= 30
Split Flow Tol= 0.02
Split Flow Ratio= 0.02
Log Output Level= 0
Friction Slope Method= 1
Unsteady Friction Slope Method= 2
Unsteady Bridges Friction Slope Method= 1
Parabolic Critical Depth
Global Vel Dist= 0 , 0 , 0
Global Log Level= 0
CheckData=False
Encroach Param=-1 ,0,0, 0
Mapping Interval=1HOUR
Run HTab= 0
Run UNet= 0
Run Sediment= 0
Run PostProcess= 0
Run WQNet= 0
Run RASMapper= 0
UNET Theta= 0
UNET Theta Warmup= 0
UNET ZTol= 0
UNET ZSATol= 0
UNET MxIter= 0
UNET Max Iter WO Improvement= 0
UNET MaxInSteps= 0
UNET DtIC= 0
UNET DtMin= 0
UNET MaxCRTS= 0
UNET WFStab= 0
UNET SFStab= 0
UNET WFX= 1
UNET SFX= 1
UNET DSS MLevel= 1
UNET Pardiso=0
UNET DZMax Abort= 0
UNET Use Existing IB Tables= 0
UNET Froude Reduction=False
UNET Froude Limit= 0
UNET Froude Power= 0
UNET Time Slicing=0,0, 5
UNET D1 Cores= 0
UNET D2 Coriolis=0
UNET D2 Cores= 0
UNET D2 Theta= 1
UNET D2 Theta Warmup= 1
UNET D2 Z Tol= 0.01
UNET D2 Volume Tol= 0.01
UNET D2 Max Iterations= 20
UNET D2 Equation= 0
UNET D2 RampUpFraction=0.1
UNET D2 TimeSlices= 1
UNET D2 BCVolumeCheck=0
UNET D1D2 MaxIter= 0
UNET D1D2 ZTol=0.01
UNET D1D2 QTol=0.1
UNET D1D2 MinQTol=1
Write IC File= 0
Write IC File at Fixed DateTime=0
Write IC File at Sim End=0
Echo Input=False
Echo Parameters=False
Echo Output=False
Write Detailed= 0
HDF Write Warmup=0
HDF Write Time Slices=0
HDF Flush=0
HDF Face Node Velocities=0
HDF Compression= 1
HDF Chunk Size= 1
HDF Spatial Parts= 1
HDF Use Max Rows=0
HDF Fixed Rows= 1
Calibration Method= 0
Calibration Iterations= 20
Calibration Max Change=0.05
Calibration Tolerance=0.2
Calibration Maximum=1.5
Calibration Minimum=0.5
Calibration Optimization Method= 1
WQ AD Non Conservative
WQ ULTIMATE=-1
WQ Max Comp Step=1HOUR
WQ Output Interval=15MIN
WQ Output Selected Increments= 0
WQ Output face flow=0
WQ Output face velocity=0
WQ Output face area=0
WQ Output face dispersion=0
WQ Output cell volume=0
WQ Output cell surface area=0
WQ Output cell continuity=0
WQ Output cumulative cell continuity=0
WQ Output face conc=0
WQ Output face dconc_dx=0
WQ Output face courant=0
WQ Output face peclet=0
WQ Output face adv mass=0
WQ Output face disp mass=0
WQ Output cell mass=0
WQ Output cell source sink temp=0
WQ Output nsm pathways=0
WQ Output nsm derived pathways=0
WQ Output MaxMinRange=-1
WQ Daily Max Min Mean=-1
WQ Daily Range=0
WQ Daily Time=0
WQ Create Restart=0
WQ Fixed Restart=0
WQ System Summary=0
WQ Write To DSS=0
WQ Use Fixed Temperature=0
Sorting and Armoring Iterations= 10
XS Update Threshold= 0.02
Bed Roughness Predictor= 0
Hydraulics Update Threshold= 0.02
Energy Slope Method= 1
Volume Change Method= 1
Sediment Retention Method= 0
XS Weighting Method= 0
Number of US Weighted Cross Sections= 1
Number of DS Weighted Cross Sections= 1
Upstream XS Weight=0
Main XS Weight=1
Downstream XS Weight=0
Number of DS XS's Weighted with US Boundary= 1
Upstream Boundary Weight= 1
Weight of XSs Associated with US Boundary= 0
Number of US XS's Weighted with DS Boundary= 1
Downstream Boundary Weight= 0.5
Weight of XSs Associated with DS Boundary= 0.5
Percentile Method= 0
Sediment Output Level= 4
Mass or Volume Output= 0
Output Increment Type= 1
Profile and TS Output Increment= 1
XS Output Flag= 0
XS Output Increment= 10
Write Gradation File= 0
Read Gradation Hotstart= 0
Write HDF5 File= 1
Write DSS Sediment File= 0
SV Curve= 0
Specific Gage Flag= 0

--- GREENBRRV1.p01 (plan) ---

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Plan Title=Calibrated Model
Program Version=5.07
Short Identifier=Calibrated model
Geom File=g01
Flow File=f01
CheckData=True
Computation Interval=0.1SEC
Output Interval=1MIN
Instantaneous Interval=Max Profile
Computation Time Step Use Courant=        0
Computation Time Step Use Time Series=    0
Computation Time Step Count To Double=0
Computation Time Step Max Doubling=0
Computation Time Step Max Halving=0
Computation Time Step Residence Courant=0
UNET 1D Methodology=Finite Difference
DSS File=dss
Write Binary Output= 1

--- GREENBRRV1.p03 (plan) ---

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Plan Title=Floodway
Program Version=4.10
Short Identifier=Floodway
Geom File=g01
Flow File=f02
CheckData=True
Encroach Param=-1 ,0,0, 2
Encroach River=GREENBRRV1
Encroach Reach=Main
Encroach Node=42803
       1     635     855
Encroach Node=41780
       1     630     850
Encroach Node=40965
       1     490     720
Encroach Node=40431
       1     420     630
Encroach Node=39483
       1     260     510
Encroach Node=38446
       1     445     715
Encroach Node=37505
       1     680     940
Encroach Node=36653
       1     665     930
Encroach Node=35777
       1     513     838
Encroach Node=34936
       1     335     680
Encroach Node=34181
       1     190     540
Encroach Node=33158
       1     215     505
Encroach Node=32627
       1     145     460
Encroach Node=32040
       1     140     460
Encroach Node=31548
       1     205     550
Encroach Node=30702
       1     270     630
Encroach Node=30077
       1     236     755
Encroach Node=29673
       1     290     850
Encroach Node=29110
       1     272     830
Encroach Node=28571
       1     240     850
Encroach Node=28156
       1     262     856
Encroach Node=27986
       1     330     853
Encroach Node=27028
       1     350     720
Encroach Node=26610
       1   625.1    1060
Encroach Node=26157
       1     330     830
Encroach Node=26006
       1     593    1090
Encroach Node=25836
       1     833    1315
Encroach Node=25741
       1     836    1298
Encroach Node=25459
       1    1155    1655
Encroach Node=24899
       1     895    1429
Encroach Node=24476
       1     698    1223
Encroach Node=24166
       1     534    1009
Encroach Node=23791
       1     691  1103.5
Encroach Node=23549
       1     583 1044.65
Encroach Node=23007
       1     450    1468
Encroach Node=22471
       1     880    2157
Encroach Node=21733
       1    1258    2205
Encroach Node=21231
       1    1379    2510
Encroach Node=20843
       1    1492    2525
Encroach Node=20212
       1    1830    2444
Encroach Node=18976
       1    1630    2161
Encroach Node=17934
       1    1879    2460
Encroach Node=16755
       1    1100    1770
Encroach Node=15974
       1    1140    1700
Encroach Node=14902
       1    1100    1685
Encroach Node=13447
       1     350     797
Encroach Node=12545
       1     750    1365
Encroach Node=11287
       1     750    2200
Encroach Node=9946
       1     780    2010
Encroach Node=8724
       1    1050    1860
Encroach Node=7288
       1     640    1420
Encroach Node=6138
       1    1850    2450
Encroach Node=4840
       1    1450    1915
UNET Convert EG Bridges= 0
UNET Junction Losses=0
WQ Output cell source sink nsm=0
Disregard all LS=0
Disregard all Conn=0
Disregard all Breaches=0
Disregard all Pumps=0

--- GREENBRRV1.f03 (steady flow) ---

Flow Title=WV 2010 Gage Flows
Program Version=5.07
Number of Profiles= 6
Profile Names=P100yr,P10yr,P25yr,P50yr,P101yr,P500yr
River Rch & RM=GREENBRRV1,Main            ,42803
   81990   55540   66240   74140   90520  100300
River Rch & RM=GREENBRRV1,Main            ,20212
   85078   57252   68299   76615   93929  105420
Boundary for River Rch & Prof#=GREENBRRV1,Main            , 1
Up Type= 0
Dn Type= 3
Dn Slope=0.00185
Boundary for River Rch & Prof#=GREENBRRV1,Main            , 2
Up Type= 0
Dn Type= 3
Dn Slope=0.00185
Boundary for River Rch & Prof#=GREENBRRV1,Main            , 3
Up Type= 0
Dn Type= 3
Dn Slope=0.00185
Boundary for River Rch & Prof#=GREENBRRV1,Main            , 4
Up Type= 0
Dn Type= 3
Dn Slope=0.00185
Boundary for River Rch & Prof#=GREENBRRV1,Main            , 5
Up Type= 0
Dn Type= 3
Dn Slope=0.00185
Boundary for River Rch & Prof#=GREENBRRV1,Main            , 6
Up Type= 0
Dn Type= 3
Dn Slope=0.00185
Observed WS=GREENBRRV1      ,Main            ,30702   ,,1555.8,,,,,
Observed WS=GREENBRRV1      ,Main            ,30077   ,,1554.9,,,,,
Observed WS=GREENBRRV1      ,Main            ,28571   ,,1553.9,,,,,
Observed WS=GREENBRRV1      ,Main            ,27986   ,,1552.5,,,,,
Observed WS=GREENBRRV1      ,Main            ,27028   ,,1551.3,,,,,
Observed WS=GREENBRRV1      ,Main            ,26610   ,,1551.2,,,,,
Observed WS=GREENBRRV1      ,Main            ,26157   ,,1551.1,,,,,
Observed WS=GREENBRRV1      ,Main            ,26006   ,,1551,,,,,
Observed WS=GREENBRRV1      ,Main            ,25836   ,,1550.8,,,,,
Observed WS=GREENBRRV1      ,Main            ,25741   ,130,1551,,,,,
Observed WS=GREENBRRV1      ,Main            ,24899   ,,1550.1,,,,,
Observed WS=GREENBRRV1      ,Main            ,24476   ,,1549.8,,,,,
Observed WS=GREENBRRV1      ,Main            ,24166   ,,1549.8,,,,,
Observed WS=GREENBRRV1      ,Main            ,23791   ,,1549.3,,,,,
Observed WS=GREENBRRV1      ,Main            ,23007   ,,1549.2,,,,,
Observed WS=GREENBRRV1      ,Main            ,22471   ,,1549.2,,,,,
Observed WS=GREENBRRV1      ,Main            ,21231   ,,1547.8,,,,,
Observed WS=GREENBRRV1      ,Main            ,20212   ,,1547.5,,,,,
Observed WS=GREENBRRV1      ,Main            ,18976   ,,1544.3,,,,,
DSS Import GetInterval= 0
DSS Import GetPeak= 0
DSS Import FillOption= 0

--- GREENBRRV1.f01 (steady flow) ---

Flow Title=Gage weighting
Program Version=5.07
Number of Profiles= 1
Profile Names=June16
River Rch & RM=GREENBRRV1,Main            ,42803
   80700
River Rch & RM=GREENBRRV1,Main            ,20212
   81660
Boundary for River Rch & Prof#=GREENBRRV1,Main            , 1
Up Type= 0
Dn Type= 3
Dn Slope=0.00185
Observed WS=GREENBRRV1      ,Main            ,30702   ,,1555.8
Observed WS=GREENBRRV1      ,Main            ,30077   ,,1554.9
Observed WS=GREENBRRV1      ,Main            ,28571   ,,1553.9
Observed WS=GREENBRRV1      ,Main            ,27986   ,,1552.5
Observed WS=GREENBRRV1      ,Main            ,27028   ,,1551.3
Observed WS=GREENBRRV1      ,Main            ,26610   ,,1551.2
Observed WS=GREENBRRV1      ,Main            ,26157   ,,1551.1
Observed WS=GREENBRRV1      ,Main            ,26006   ,,1551
Observed WS=GREENBRRV1      ,Main            ,25836   ,,1550.8
Observed WS=GREENBRRV1      ,Main            ,25741   ,130,1551
Observed WS=GREENBRRV1      ,Main            ,24899   ,,1550.1
Observed WS=GREENBRRV1      ,Main            ,24476   ,,1549.8
Observed WS=GREENBRRV1      ,Main            ,24166   ,,1549.8
Observed WS=GREENBRRV1      ,Main            ,23791   ,,1549.3
Observed WS=GREENBRRV1      ,Main            ,23007   ,,1549.2
Observed WS=GREENBRRV1      ,Main            ,22471   ,,1549.2
Observed WS=GREENBRRV1      ,Main            ,21231   ,,1547.8
Observed WS=GREENBRRV1      ,Main            ,20212   ,,1547.5
Observed WS=GREENBRRV1      ,Main            ,17934   ,,1544.3
DSS Import GetInterval= 0
DSS Import GetPeak= 0
DSS Import FillOption= 0

--- GREENBRRV1.f02 (steady flow) ---

Flow Title=WV 2010 Gage Flows
Program Version=5.07
Number of Profiles= 2
Profile Names=P100yr,Floodway
River Rch & RM=GREENBRRV1,Main            ,42803
   81990   81990
River Rch & RM=GREENBRRV1,Main            ,20212
   85078   85078
Boundary for River Rch & Prof#=GREENBRRV1,Main            , 1
Up Type= 0
Dn Type= 3
Dn Slope=0.00185
Boundary for River Rch & Prof#=GREENBRRV1,Main            , 2
Up Type= 0
Dn Type= 3
Dn Slope=0.00185
DSS Import GetInterval= 0
DSS Import GetPeak= 0
DSS Import FillOption= 0

--- GREENBRRV1.g01 (geometry) ---

Geom Title=LiDAR Data
Program Version=4.10

River Reach=GREENBRRV1      ,Main
Reach XY= 30
     2147853.903288318.4270000012140252.74700004285074.931000009
2137992.79400003 282569.211000012135001.75099999283721.890000001
2132578.70100001282382.5550000222126465.11000004273568.732999995
2123999.83200002271443.7329999952118701.22099999269881.232999995
2117263.72099999266277.0660000152113214.12500003262937.376000017
2109857.02700001263954.0929999952107051.02300003267747.055000007
2105756.61700001264284.1519999952103657.17400002264126.947000012
2102670.62800002265781.803000018     2104764.748269176.392000005
2104439.43399999272526.3110000192102946.13100001273330.069000021
     2099868.465271235.2929999982099273.02200001274387.615999997
2095783.85699999273525.3990000192095268.35600001270575.908000022
2091072.92199999269744.2960000192079295.30000004260919.210000008
2075461.96599999263486.918000013 2063780.6355315266298.942803565
2062392.85613854265132.9219733962064349.69214562260340.365448384
2064375.00635672253981.9608957772061134.39771583253178.862430432

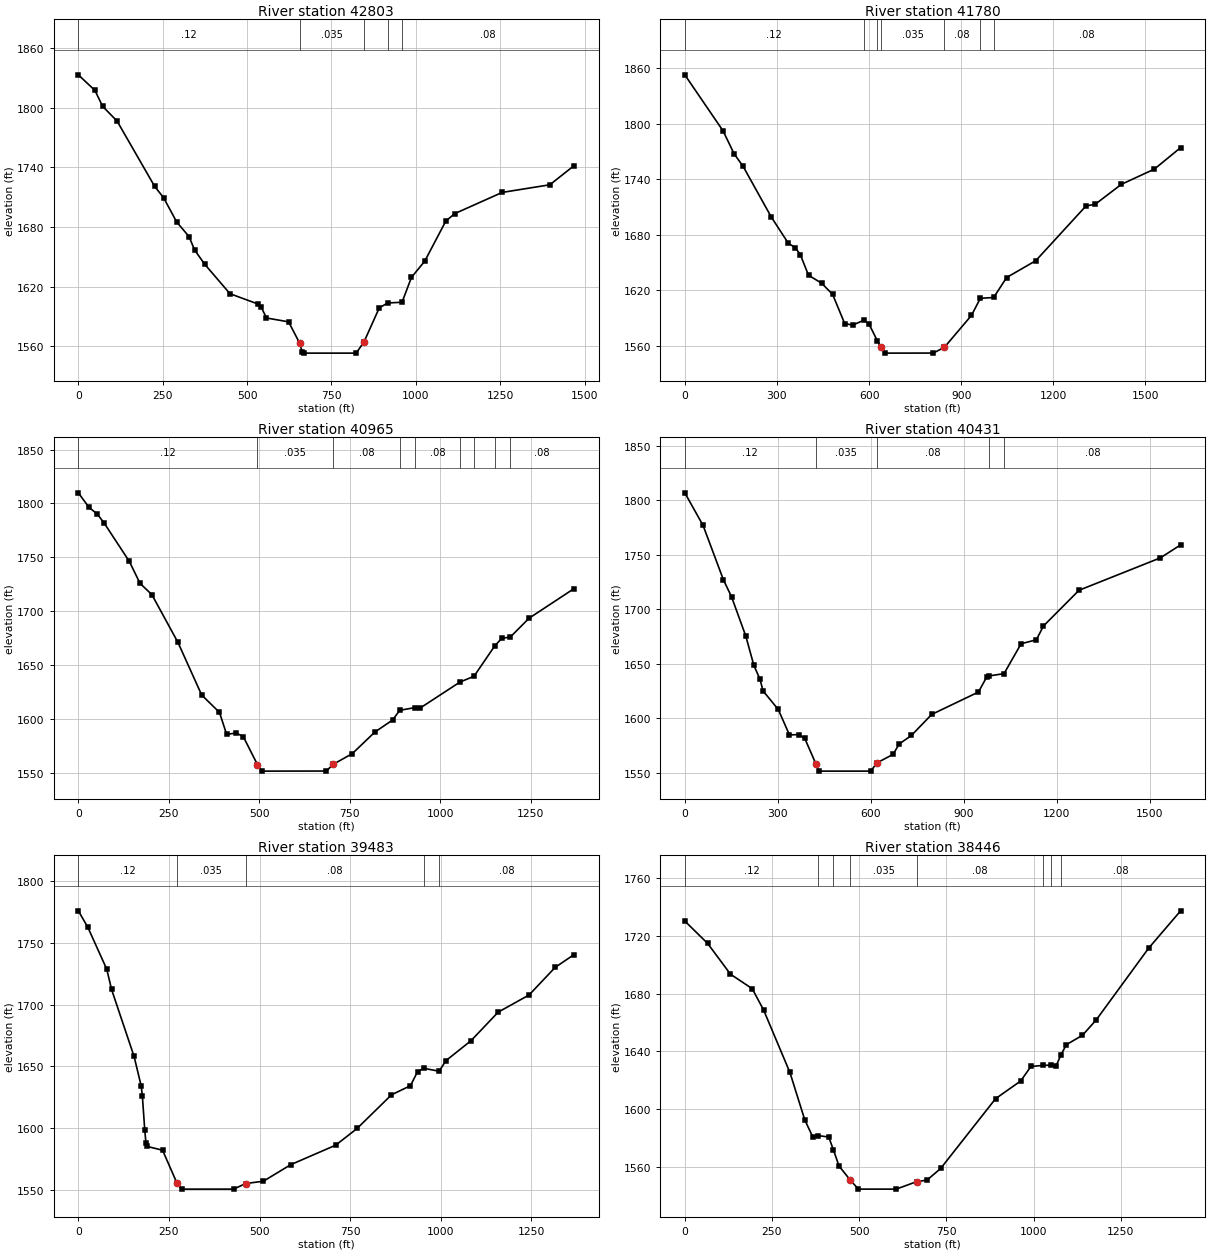
Type RM Length L Ch R = 1 ,42803   ,1026,1022.6,1023.1
Node Name=F
XS GIS Cut Line= 2
     2086136.156      265455.813      2085015.93      266406.117
#Sta/Elev= 30
       0 1832.92    49.2 1817.22    72.1 1801.18   114.8  1786.4   226.2 1720.67
   252.5 1709.36   291.8 1684.69   327.9 1670.31   344.3 1656.89   373.8 1642.67
   449.2 1612.79   531.2 1602.54     541 1599.87   557.4 1588.37     623 1584.48
   655.8 1562.96   663.7  1553.8   668.9 1553.02     823 1553.02     846 1564.03
   891.9 1598.75   917.2 1603.48   959.1 1604.18     987 1629.26  1026.3 1645.49
  1088.6 1685.75  1114.9 1693.28  1255.9 1714.67  1396.9 1722.33    1469 1741.65
#Mann= 5 ,-1 , 0
       0     .12       0   655.8    .035       0     846     .08       0
   917.2    .016       0   959.1     .08       0
Bank Sta=655.8,846
XS Rating Curve= 0 ,0
Exp/Cntr=0.3,0.1

Type RM Length L Ch R = 1 ,41780   ,817.9,814.6,800.4
XS GIS Cut Line= 2
     2085450.175      264681.724     2084235.548      265745.309
#Sta/Elev= 30
       0 1852.66   124.4 1792.28   160.5 1767.46   189.9 1753.88   281.6 1699.22
   337.3 1670.81   360.2 1666.14   376.6  1658.3   402.8 1636.42   445.4 1627.86
   481.4 1615.72   520.7 1584.22   546.9 1582.64   582.9 1587.84   599.3 1584.16
   626.7 1565.84   638.6 1559.16   651.7 1552.37   808.9 1552.44   844.9 1558.49
   933.3    1593   962.3  1611.5  1005.8 1612.42  1047.9 1633.94  1142.9 1652.12
  1306.6 1711.27  1336.1 1712.91  1421.3 1734.46  1529.3 1750.98  1614.5 1774.13
#Mann= 7 ,-1 , 0
       0     .12       0   582.9     .08       0   626.7     .06       0
   638.6    .035       0   844.9     .08       0   962.3    .016       0
  1005.8     .08       0
Bank Sta=638.6,844.9
XS Rating Curve= 0 ,0
Exp/Cntr=0.3,0.1

Type RM Length L Ch R = 1 ,40965   ,518.9,534.2,567.7
XS GIS Cut Line= 2
     2084801.955      264121.611     2083832.771      265090.795
#Sta/Elev= 30
       0 1809.85    29.5 1796.34    52.5 1790.16    72.1 1781.46     141 1746.25
   170.5 1725.93   203.3 1715.46   275.4 1671.16     341 1622.41   390.2 1606.28
   409.9 1585.92   436.1 1587.19   455.8 1583.95   495.1 1557.94   508.2 1551.86
   685.3 1551.94     705 1558.25   757.5 1568.14   819.8 1588.11   868.9 1599.28
   888.3 1608.22   931.9 1610.83   944.4 1610.24  1054.8 1634.39  1093.8 1639.82
  1151.6 1668.19  1170.6    1675  1194.1 1676.14    1246 1693.62  1370.6 1721.13
#Mann= 9 ,-1 , 0
       0     .12       0   495.1    .035       0     705     .08       0
   888.3    .016       0   931.9     .08       0  1054.8    .016       0
  1093.8     .08       0  1151.6    .016       0  1194.1     .08       0
Bank Sta=495.1,705
XS Rating Curve= 0 ,0
Exp/Cntr=0.3,0.1

Type RM Length L Ch R = 1 ,40431   ,987.9,948.5,864.4
Node Name=E
XS GIS Cut Line= 2
     2084556.512      263775.474     2083234.897      264675.431
#Sta/Elev= 30
       0 1806.94      59 1776.96   124.5 1727.08   150.7 1711.51   196.6 1675.47
   222.8 1648.45   242.5 1635.78   252.3  1625.1   301.4 1608.02   337.5 1584.63
     367 1584.98   386.6 1581.62   422.7  1558.1   432.5 1551.41   599.6 1551.42
   619.3  1558.9   671.7 1566.83   691.3  1576.3   730.7 1584.14   796.2 1603.48
   946.9 1624.02   973.1 1637.62   981.6 1638.85  1029.4 1640.92  1084.5 1668.37
  1133.7 1672.01  1156.6 1684.69  1271.3 1717.47  1533.4 1747.19  1598.9 1759.14
#Mann= 5 ,-1 , 0
       0     .12       0   422.7    .035       0   619.3     .08       0
   981.6    .016       0  1029.4     .08       0
Bank Sta=422.7,619.3
XS Rating Curve= 0 ,0
Exp/Cntr=0.3,0.1

Type RM Length L Ch R = 1 ,39483   ,1075.1,1036.8,936.8
XS GIS Cut Line= 2
     2083681.729      263058.026     2083052.389      264272.653
#Sta/Elev= 30
       0 1775.89    26.2 1762.58    78.5 1728.54    91.6  1712.3   153.8 1657.96
   173.4 1634.12   176.7  1625.9   183.3 1598.21   186.5 1588.06   189.8 1585.11
   232.4 1582.02   271.6 1555.74   284.7 1550.51   428.7 1550.52   461.4 1555.02
   510.5 1556.91   585.8 1570.28   710.2 1586.13   769.1 1599.63     864 1626.88
   916.4 1634.29     936 1645.66   952.4 1648.39   995.4    1646  1014.5 1654.62
  1083.3 1670.69  1158.5 1693.87  1243.6 1707.74  1315.6 1730.08    1368 1740.51
#Mann= 5 ,-1 , 0
       0     .12       0   271.6    .035       0   461.4     .08       0
   952.4    .016       0   995.4     .08       0
Bank Sta=271.6,461.4
XS Rating Curve= 0 ,0
Exp/Cntr=0.3,0.1

Type RM Length L Ch R = 1 ,38446   ,852.8,941.2,1042.4
XS GIS Cut Line= 2
     2082473.396      262661.542     2082599.264      264077.558
#Sta/Elev= 30
       0 1730.38    65.5 1714.85     131 1693.52   193.3 1683.48     226 1668.66
   301.4 1625.38   343.9 1592.59   366.9 1580.69   382.5 1581.63   412.7 1580.62
   426.1 1571.73   442.2 1560.52     475 1550.61   497.9 1544.51     606 1544.51
   664.9 1549.69   694.4 1550.76   733.7 1558.86     891 1607.21     963 1619.48
   992.5 1629.59  1027.9 1630.27  1048.8  1630.5  1064.6 1629.93  1078.5 1637.61
    1094 1644.67  1139.9 1651.13  1179.2  1661.7  1329.9 1711.57  1421.6 1737.46
#Mann= 8 ,-1 , 0
       0     .12       0   382.5     .08       0   426.1     .12       0
     475    .035       0   664.9     .08       0  1027.9    .016       0
  1048.8     .08       0  1078.5     .08       0
Bank Sta=475,664.9
XS Rating Curve= 0 ,0
Exp/Cntr=0.3,0.1

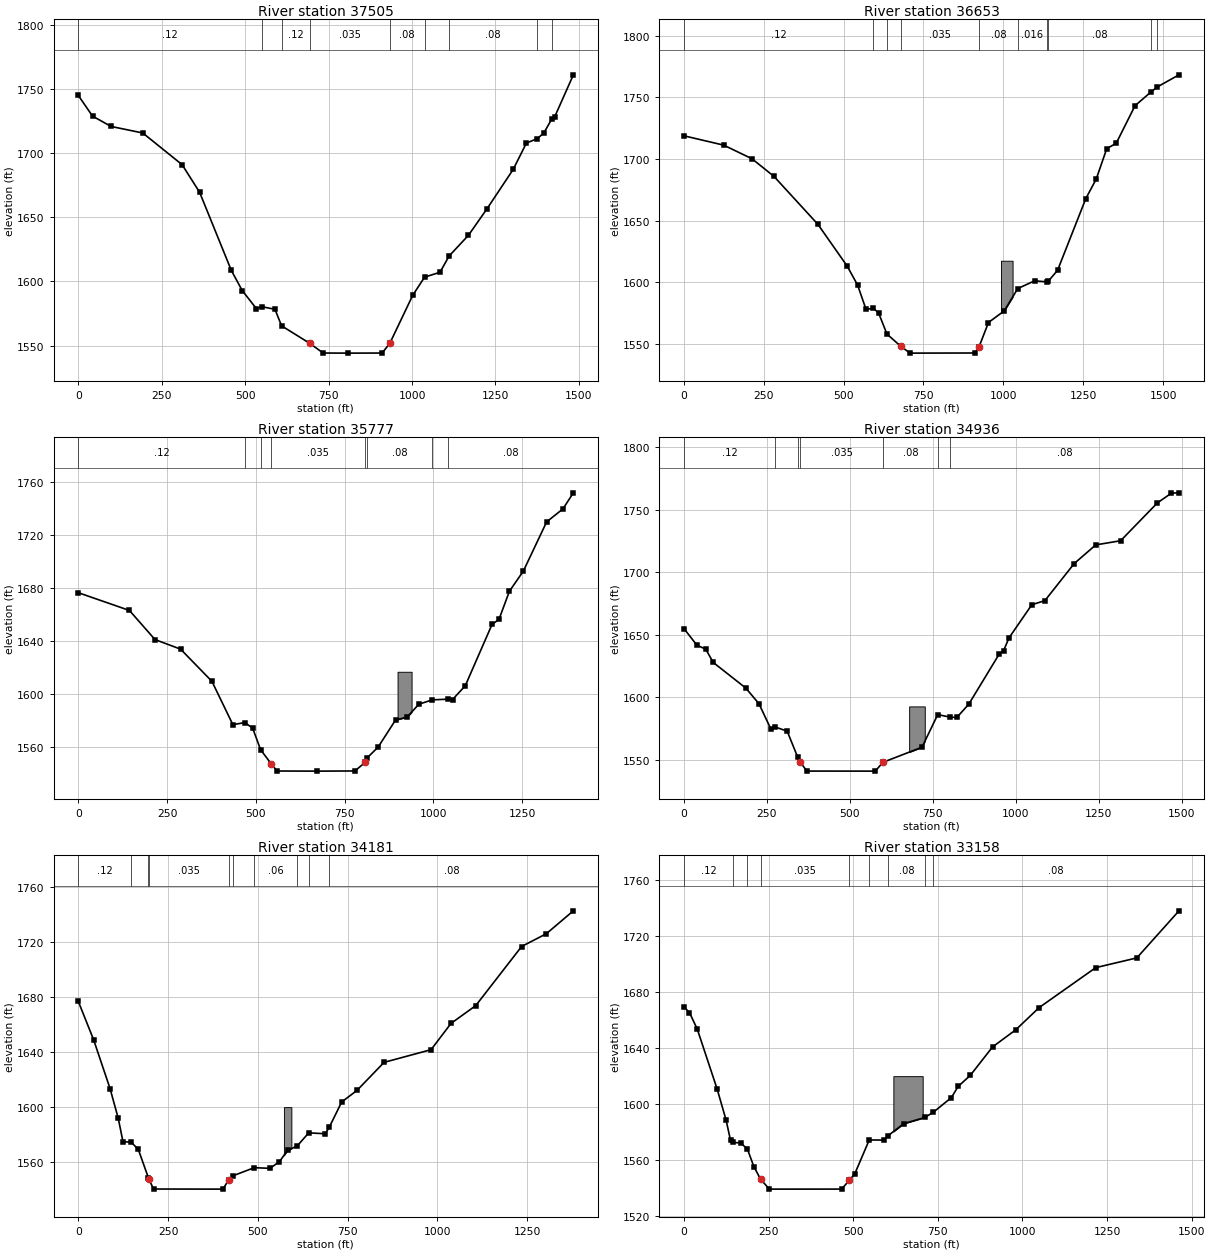
Type RM Length L Ch R = 1 ,37505   ,839.6,851.4,864.6
XS GIS Cut Line= 2
     2082190.192      262422.393     2081189.541      263517.444
#Sta/Elev= 30
       0 1745.32    42.6 1729.18    98.2 1721.08   193.2 1715.98   311.1 1691.22
   363.5 1669.68   458.4 1608.71   491.2 1592.92   533.8 1578.77   549.8 1580.32
   589.4 1578.28     609  1565.4   694.2 1551.59   733.5 1544.13   808.7 1544.05
   910.3 1544.12   933.3 1551.62    1002 1589.17  1037.6 1603.38  1083.9 1607.21
    1111 1619.87    1169 1636.06  1224.7 1656.79  1303.3 1687.59  1342.6 1708.08
  1375.4  1711.6    1395 1715.98  1418.3 1726.72  1427.7  1728.7  1483.4  1761.4
#Mann= 9 ,-1 , 0
       0     .12       0   549.8     .08       0     609     .12       0
   694.2    .035       0   933.3     .08       0  1037.6    .016       0
    1111     .08       0  1375.4    .016       0  1418.3     .08       0
Bank Sta=694.2,933.3
XS Rating Curve= 0 ,0
Exp/Cntr=0.3,0.1

Type RM Length L Ch R = 1 ,36653   ,896.1,875.9,863
XS GIS Cut Line= 2
      2081667.84      261843.399     2080528.734      262894.398
#Sta/Elev= 30
       0 1718.74   124.5 1711.16     213 1700.13   281.8 1685.83   419.4 1646.93
   511.2 1612.98   543.9 1597.55   570.2 1577.84   593.1 1578.85   609.5 1574.93
   635.7 1557.86   678.3  1548.1   707.8  1542.4   910.9 1542.51     924 1547.56
   953.5 1567.25  1002.7 1576.67  1045.3 1594.81  1097.7 1601.05  1135.3 1600.26
  1140.3 1600.61  1169.8 1609.61  1258.3 1667.83    1291 1683.73  1323.8 1708.37
  1353.3 1712.62  1412.3 1743.15  1461.4 1754.12  1482.4 1758.44  1549.9 1768.21
#Mann= 10 ,-1 , 0
       0     .12       0   593.1     .08       0   635.7     .12       0
   678.3    .035       0     924     .08       0  1045.3    .016       0
  1135.3     .08       0  1140.3     .08       0  1461.4    .016       0
  1482.4     .08       0
#Block Obstruct= 1 ,-1
  992.71 1028.941617.375
Bank Sta=678.3,924
XS Rating Curve= 0 ,0
Exp/Cntr=0.3,0.1

Type RM Length L Ch R = 1 ,35777   ,856.3,841.5,827.6
XS GIS Cut Line= 2
     2080918.925      261220.353     2080025.262      262290.231
#Sta/Elev= 30
       0 1676.32     144  1662.9     216  1640.9     288 1633.68   376.3 1609.34
   435.2 1576.63   468.5 1578.16   490.8 1574.11   513.2 1557.76   543.2 1547.04
   559.6  1541.6   670.8 1541.51   778.8 1541.63   808.3 1548.22   814.2 1551.73
   844.3 1559.68   893.4 1580.16   926.1 1582.36   958.8 1592.06   996.8 1595.36
  1041.5 1595.87  1053.7 1595.54  1089.7 1606.05    1165 1652.34  1184.6 1656.16
    1214 1677.43  1253.3  1692.7  1318.8 1729.84  1364.6  1739.6    1394 1751.77
#Mann= 8 ,-1 , 0
       0     .12       0   468.5     .08       0   513.2     .12       0
   543.2    .035       0   808.3     .08       0   814.2     .08       0
   996.8    .016       0  1041.5     .08       0
#Block Obstruct= 1 ,-1
  898.99  938.481616.584
Bank Sta=543.2,808.3
XS Rating Curve= 0 ,0
Exp/Cntr=0.3,0.1

Type RM Length L Ch R = 1 ,34936   ,814.7,755.1,650.3
XS GIS Cut Line= 3
     2080094.489      260823.868     2079446.269      261774.172
      2079521.79      262107.722
#Sta/Elev= 30
       0 1654.91    39.3 1641.54    65.6 1638.46    88.5 1627.76   186.8 1607.25
   226.1 1594.82   262.2 1574.52   275.1 1576.18   311.3 1572.86   342.5 1552.34
   350.7 1548.24   370.3 1540.96   576.8 1540.91   599.8 1547.94   717.7 1560.05
   765.1 1586.09     802 1584.11   822.6  1583.8   858.6 1594.39   950.4 1634.49
   963.5 1637.15   979.9 1647.44  1048.7 1673.93  1088.1 1677.22  1176.4 1706.83
  1241.5 1721.78  1316.4  1725.1  1427.2 1755.35  1469.5 1763.14  1492.3  1763.4
#Mann= 7 ,-1 , 0
       0     .12       0   275.1     .08       0   342.5     .06       0
   350.7    .035       0   599.8     .08       0   765.1    .016       0
     802     .08       0
#Block Obstruct= 1 ,-1
  678.94  726.011592.663
Bank Sta=350.7,599.8
XS Rating Curve= 0 ,0
Exp/Cntr=0.3,0.1

Type RM Length L Ch R = 1 ,34181   ,1086,1022.8,908.2
XS GIS Cut Line= 2
     2079156.772      260616.186     2079125.305      261994.441
#Sta/Elev= 30
       0 1676.92    42.6 1649.06    88.4 1613.56   111.3 1591.83   124.4 1574.94
   147.4 1574.48     167 1569.38   195.3 1548.55   196.5 1547.66   209.6 1540.49
   402.8 1540.41   419.2 1547.33   432.2 1550.26     490 1556.01   533.8 1555.53
     560 1560.34   582.9 1568.68   608.9 1571.61   641.8 1581.35   687.7 1580.66
   699.4  1585.7   733.5 1603.78   776.1  1612.2   851.4 1632.57   982.4 1641.82
    1038 1660.93  1106.8 1673.86  1234.5 1716.83  1303.3 1726.11  1378.6 1742.77
#Mann= 10 ,-1 , 0
       0     .12       0   147.4     .08       0   195.3     .12       0
   196.5    .035       0   419.2     .08       0   432.2     .08       0
     490     .06       0   608.9     .08       0   641.8    .016       0
   699.4     .08       0
#Block Obstruct= 1 ,-1
   572.6  593.361600.028
Bank Sta=196.5,419.2
XS Rating Curve= 0 ,0
Exp/Cntr=0.3,0.1

Type RM Length L Ch R = 1 ,33158   ,538.3,531.2,523.6
Node Name=D
XS GIS Cut Line= 2
     2077986.199       260956.03     2078854.689      262132.896
#Sta/Elev= 30
       0 1669.58    16.4 1665.46    39.4 1653.72    98.4 1610.68   124.6 1588.69
   137.7 1574.26   145.3 1572.75   167.2 1572.38   187.3 1568.18   206.6 1555.52
   226.3 1546.55   252.5  1539.4   465.7 1539.43   488.6 1545.62     505 1550.48
   547.5 1574.51   590.3 1574.43   603.4  1577.6   649.3 1586.17   711.5 1590.57
   736.6 1594.25   790.4 1604.82     810  1612.7   846.1 1620.65   911.7 1640.92
   980.6 1653.22  1049.4 1669.04  1216.7 1697.59    1338 1704.53  1462.6 1738.16
#Mann= 9 ,-1 , 0
       0     .12       0   145.3     .08       0   187.3     .06       0
   226.3    .035       0   488.6     .08       0   547.5    .016       0
   603.4     .08       0   711.5    .016       0   736.6     .08       0
#Block Obstruct= 1 ,-1
   618.8  705.431620.081
Bank Sta=226.3,488.6
XS Rating Curve= 0 ,0
Exp/Cntr=0.3,0.1

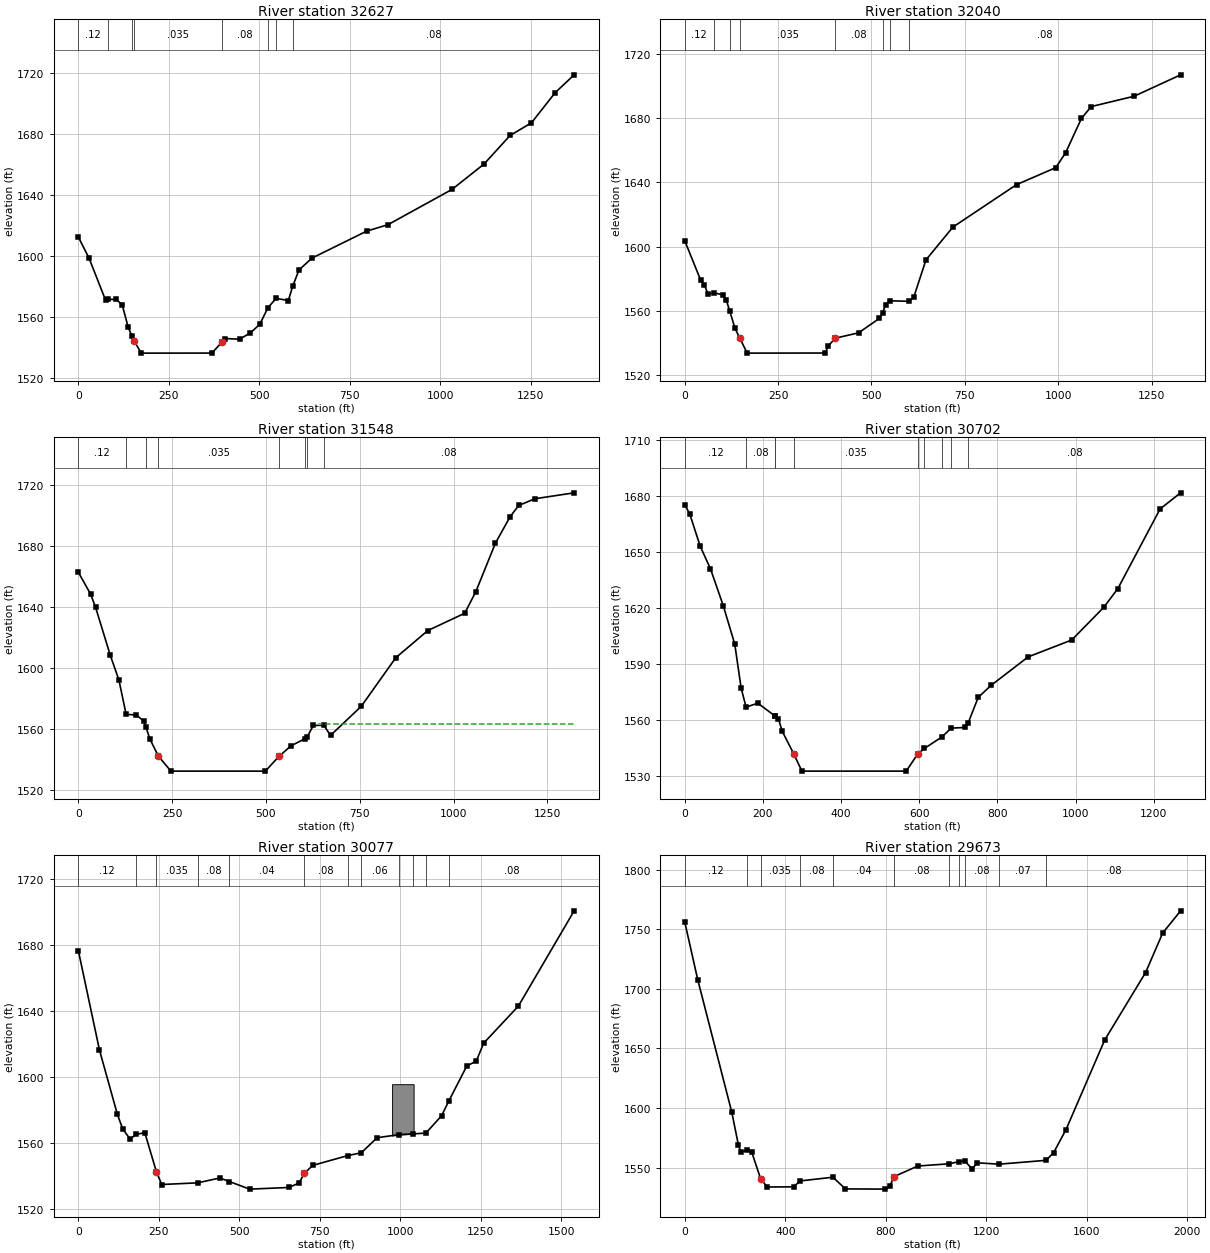
Type RM Length L Ch R = 1 ,32627   ,589.1,587.3,573.8
XS GIS Cut Line= 2
     2077551.955        261270.7     2078407.858      262340.578
#Sta/Elev= 30
       0 1612.45    29.5 1598.64    75.4 1570.88    81.8 1571.49   104.9 1571.46
   121.3 1567.82   137.7 1553.23   147.5 1547.58   154.1 1544.28   173.7 1536.14
   369.2 1536.17   396.6 1543.34   406.4 1545.71   445.8 1545.31   475.3 1549.43
   501.5 1555.08   523.6 1565.89   546.5 1572.16   580.2 1570.72     593 1580.44
   609.7 1590.83   645.7 1598.62   796.5 1616.32   855.5 1620.57  1032.5 1643.75
    1121 1660.44  1193.1 1679.24  1252.1 1687.54  1317.7 1707.39  1370.1  1719.1
#Mann= 8 ,-1 , 0
       0     .12       0    81.8     .08       0   147.5     .12       0
   154.1    .035       0   396.6     .08       0   523.6     .06       0
   546.5    .016       0     593     .08       0
Bank Sta=154.1,396.6
XS Rating Curve= 0 ,0
Exp/Cntr=0.3,0.1

Type RM Length L Ch R = 1 ,32040   ,499.8,491.6,482.9
XS GIS Cut Line= 2
     2077111.417      261673.478     2077998.786      262661.542
#Sta/Elev= 30
       0 1603.59    42.6 1579.02    52.5  1576.2    62.3 1570.21    77.2 1571.23
   101.6 1569.94   111.5  1566.4   120.7 1559.52   134.4 1549.06   147.6 1542.73
   167.2 1533.55   376.6 1533.62   383.7 1537.96   403.3 1542.88   465.6 1546.22
   521.4 1555.27   529.9 1558.69   537.8 1563.81   548.3  1566.2   600.5 1565.88
   613.2 1568.45     646 1591.75   718.1 1612.19   888.6 1638.68   993.6 1649.25
  1019.8 1658.48  1062.4    1680  1088.7 1687.37  1203.4 1693.81    1328 1707.17
#Mann= 8 ,-1 , 0
       0     .12       0    77.2     .08       0   120.7     .12       0
   147.6    .035       0   403.3     .08       0   529.9     .06       0
   548.3    .016       0   600.5     .08       0
Bank Sta=147.6,403.3
XS Rating Curve= 0 ,0
Exp/Cntr=0.3,0.1

Type RM Length L Ch R = 1 ,31548   ,845.6,846.5,845.9
XS GIS Cut Line= 2
     2076702.056      261986.933     2077653.445        262903.6
#Sta/Elev= 30
       0 1662.87    32.8  1648.5    45.9 1639.94    85.2 1608.41   108.2 1592.25
   127.3  1569.8   154.1 1569.38   173.8 1565.56   180.1  1561.6   190.1 1553.95
   213.1 1542.48   246.7 1532.61   498.3 1532.61   534.4 1542.22   567.1 1549.26
   604.5 1553.93   608.9 1554.68   626.2 1562.51     654 1562.67     672 1556.02
     754 1575.11   845.8 1606.88     931 1624.66  1029.4    1636  1058.9 1650.03
  1111.3 1681.92  1150.7 1699.37  1173.6 1706.61  1216.2    1711  1321.1 1714.89
#Mann= 8 ,-1 , 0
       0     .12       0   127.3     .08       0   180.1     .12       0
   213.1    .035       0   534.4     .08       0   604.5     .06       0
   608.9    .016       0     654     .08       0
#XS Ineff= 2 , 0
                             639         1563.17
Permanent Ineff=
       F       F
Bank Sta=213.1,534.4
XS Rating Curve= 0 ,0
Exp/Cntr=0.3,0.1

Type RM Length L Ch R = 1 ,30702   ,595.7,624.2,656.5
XS GIS Cut Line= 2
     2076059.333      262540.665     2076971.876      263421.742
#Sta/Elev= 30
       0 1675.36    13.1 1670.07    39.3 1653.06    65.6 1640.97    98.3 1621.21
   127.8 1600.54   144.2 1576.91   156.8 1566.73   186.8 1568.88   230.1 1562.08
   231.8 1561.78   239.3 1560.63   249.1 1553.87   278.6 1541.74   299.6 1532.43
   566.4 1532.43   596.5 1541.79   612.9 1544.57   657.1 1550.67   681.7 1555.48
   717.8 1555.86   725.4 1558.48   750.6 1571.95   783.4 1578.38   878.4 1593.69
   989.9 1602.74  1071.8 1620.24  1107.9  1630.3    1216 1673.02  1268.5 1681.66
#Mann= 10 ,-1 , 0
       0     .12       0   156.8     .08       0   230.1     .06       0
   231.8     .12       0   278.6    .035       0   596.5     .08       0
   612.9     .08       0   657.1     .06       0   681.7    .016       0
   725.4     .08       0
Bank Sta=278.6,596.5
XS Rating Curve= 0 ,0
Exp/Cntr=0.3,0.1

Type RM Length L Ch R = 1 ,30077   ,405,404.1,404.5
XS GIS Cut Line= 3
     2075569.243      262796.829     2076246.433      263714.826
     2076550.146      263973.044
#Sta/Elev= 30
       0 1676.47    65.6 1616.39   121.3 1577.42   137.7 1568.75   160.6 1562.54
   180.3 1565.46   206.5 1566.34   242.6 1542.63     259 1535.08   370.4 1536.09
   439.2 1539.01   468.8 1536.89  531.62 1532.29  653.33 1533.28   685.1 1535.94
   701.5  1541.8   727.7 1546.64   835.9 1552.53   878.5 1554.26   927.7 1563.37
   996.5 1565.25  1040.2 1565.69    1079 1566.16  1127.6 1576.59  1150.6 1585.68
  1206.1 1606.75  1235.5 1609.65  1258.4 1620.49  1366.2 1642.92  1539.4  1700.5
#Mann= 12 ,-1 , 0
       0     .12       0   180.3     .08       0   242.6    .035       0
   370.4     .08       0   468.8     .04       0   701.5     .08       0
   835.9    .016       0   878.5     .06       0   996.5     .08       0
  1040.2    .016       0    1079     .06       0  1150.6     .08       0
#Block Obstruct= 1 ,-1
  974.13 1040.971595.716
Bank Sta=242.6,701.5
XS Rating Curve= 0 ,0
Exp/Cntr=0.3,0.1

Type RM Length L Ch R = 1 ,29673   ,519.9,563.7,660.7
Node Name=GC
XS GIS Cut Line= 4
     2075261.083      262856.725     2075229.249      262997.882
       2076146.5      264275.996     2076372.195      264397.523
#Sta/Elev= 30
       0  1756.1    51.4 1707.85   187.3 1596.32   213.5 1568.83   223.4 1562.75
   246.7 1564.71     266 1563.29     302 1540.52   328.2 1533.68   433.1 1533.79
   459.3 1538.76   589.8 1541.87  639.43 1532.06   798.2 1531.87   816.6 1534.45
     833 1542.38     928 1551.29  1052.6 1553.14  1091.9 1554.97  1114.2 1555.69
  1144.3 1548.74    1164 1553.98  1251.5 1552.82  1438.2 1556.05  1468.8 1562.59
    1518 1581.94    1672 1657.16  1834.7 1713.77  1902.8 1746.97  1974.2 1765.61
#Mann= 11 ,-1 , 0
       0     .12       0   246.7     .08       0     302    .035       0
   459.3     .08       0   589.8     .04       0     833     .08       0
  1052.6     .06       0  1091.9    .016       0  1114.2     .08       0
  1251.5     .07       0  1438.2     .08       0
Bank Sta=302,833
XS Rating Curve= 0 ,0
Exp/Cntr=0.3,0.1

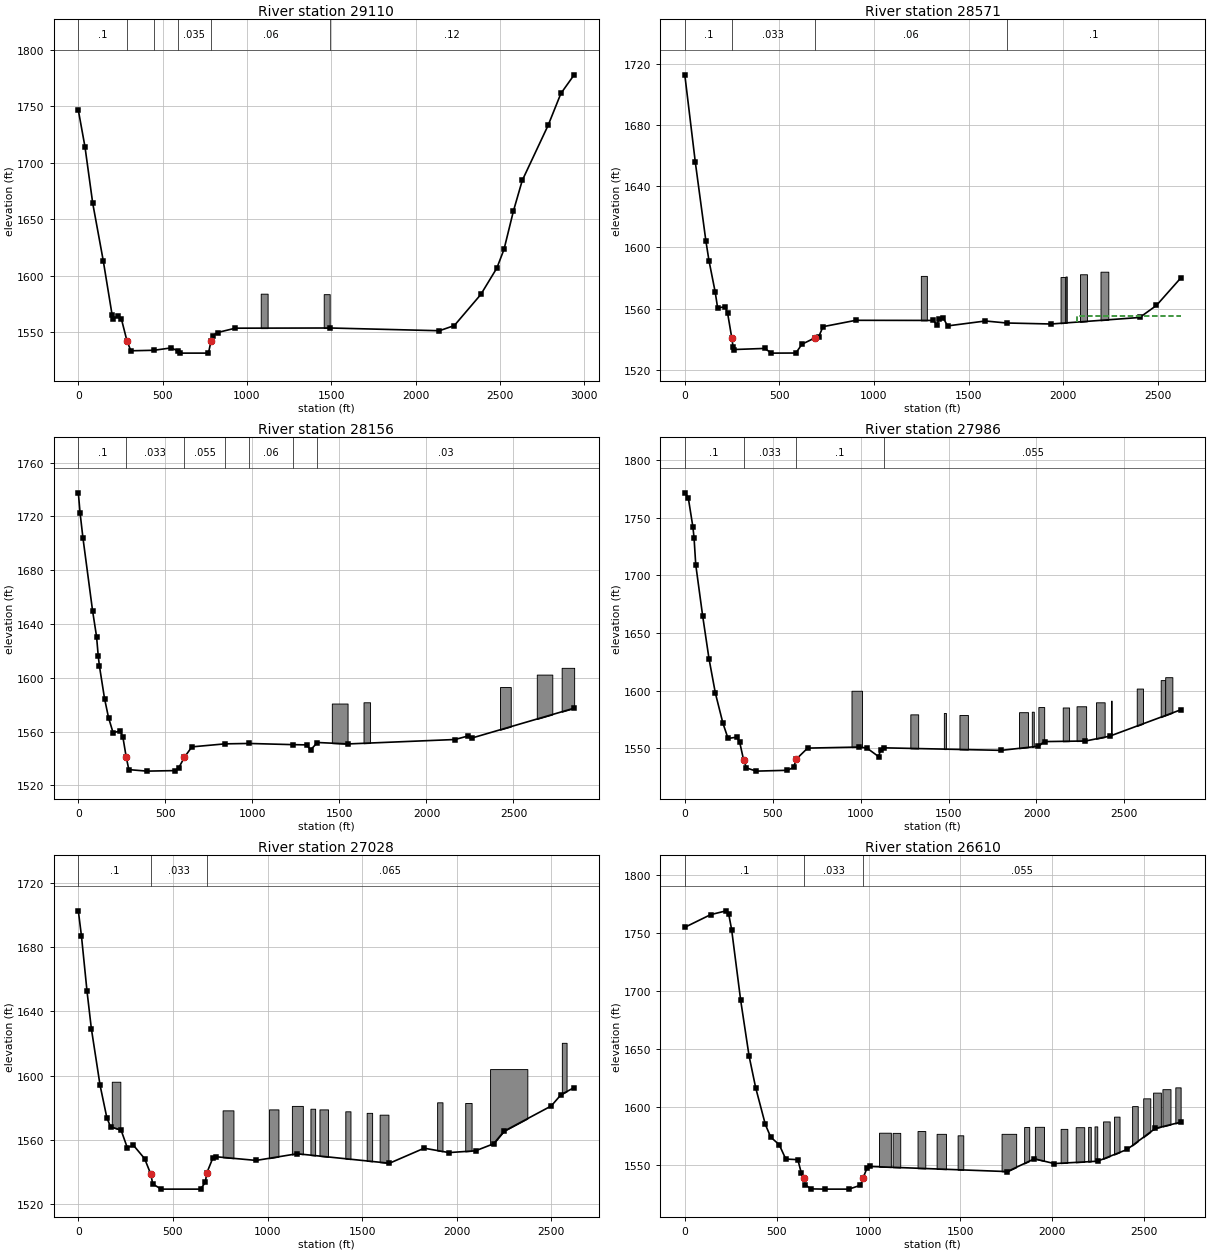
Type RM Length L Ch R = 1 ,29110   ,530.7,538.7,510.4
XS GIS Cut Line= 3
     2074787.125      262936.586     2075564.903       265193.53
     2076071.847      265415.753
#Sta/Elev= 30
       0 1746.44    39.4 1714.05    85.3 1664.12   147.6 1613.39     200 1565.56
   206.6 1562.05   236.1 1564.04   255.8 1561.42   288.6 1542.19   311.5  1533.5
   449.2 1533.96   550.9 1536.07   588.3 1533.51  604.35 1531.43  771.67 1531.45
     787 1542.08   796.8  1546.9   826.3 1549.68   931.3 1553.51  1495.3 1553.67
  2141.3 1551.25  2229.8 1555.81  2387.2 1583.36  2482.2 1606.73  2524.8 1623.33
  2580.4 1657.14  2632.8 1684.26  2786.8 1733.22  2862.1 1761.27  2940.7 1777.75
#Mann= 6 ,-1 , 0
       0      .1       0   288.6    .035       0   449.2     .08       0
   588.3    .035       0     787     .06       0  1495.3     .12       0
#Block Obstruct= 2 ,-1
 1081.81 1122.631584.046  1455.4 1490.751583.619
Bank Sta=288.6,787
XS Rating Curve= 0 ,0
Exp/Cntr=0.3,0.1

Type RM Length L Ch R = 1 ,28571   ,407.3,414.9,395.6
XS GIS Cut Line= 2
     2074305.427      262990.101     2075117.276      265482.288
#Sta/Elev= 30
       0 1712.66    55.7 1655.47   111.4 1604.24   127.8 1591.32   160.5 1570.93
   173.6 1560.44     213  1561.2   226.1 1557.13  248.37 1540.89   255.6 1534.69
   262.1 1533.29   422.6    1534  457.91 1530.93   587.3    1531   619.2 1536.75
     688 1540.88   707.7 1541.54   730.6  1548.2   904.3 1552.36  1313.8 1552.28
  1333.5 1549.48  1343.3 1553.32  1366.2 1553.87  1389.2 1548.71    1589 1551.91
  1701.2 1550.61  1936.3 1549.95  2404.8 1554.21  2493.3 1562.07  2621.1  1579.9
#Mann= 4 ,-1 , 0
       0      .1       0  248.37    .033       0     688     .06       0
  1701.2      .1       0
#XS Ineff= 2 , 0
                         2075.48         1555.29
Permanent Ineff=
       F       F
#Block Obstruct= 5 ,-1
 1247.81 1279.631581.359 1986.29 2011.211580.617 2012.43 2019.181580.971
  2089.1 2125.911582.431 2197.56  2238.81584.099
Bank Sta=248.37,688
XS Rating Curve= 0 ,0
Exp/Cntr=0.3,0.1

Type RM Length L Ch R = 1 ,28156   ,126.1,170.2,335.6
XS GIS Cut Line= 4
     2073959.115      263005.409     2073975.606      263194.507
     2074624.049      265069.465     2074905.544      265682.722
#Sta/Elev= 30
       0 1737.58     9.8 1722.92    26.2 1704.34    81.8  1649.9   104.7 1630.66
   114.5    1616   121.1 1608.85   150.5  1584.6   173.4 1570.44   199.6 1559.19
     239  1560.4   255.4 1556.35   275.1 1541.02  290.16 1531.72  393.17  1530.6
  556.71    1531  576.67    1533   609.6 1540.97   652.2 1548.64   842.4 1550.88
   980.1 1551.18  1235.9 1550.29  1311.3 1550.12  1334.3 1546.41  1373.6 1551.89
  1550.7 1550.83  2163.9 1554.12    2236 1556.63  2258.9 1555.14  2848.5 1577.42
#Mann= 7 ,-1 , 0
       0      .1       0   275.1    .033       0   609.6    .055       0
   842.4    .016       0   980.1     .06       0  1235.9      .1       0
  1373.6     .03       0
#Block Obstruct= 5 ,-1
 1456.36 1546.681580.873  1638.4 1675.961581.802 2422.43 2484.261593.129
 2633.86 2722.881602.383 2776.74 2848.51 1607.42
Bank Sta=275.1,609.6
XS Rating Curve= 0 ,0
Exp/Cntr=0.3,0.1

Type RM Length L Ch R = 1 ,27986   ,1000.3,957.9,811.2
XS GIS Cut Line= 2
     2073863.514      262978.253     2074064.903      265790.753
#Sta/Elev= 30
       0  1771.5    19.7 1767.28    45.9 1742.05    52.5 1732.77    62.3 1709.16
   101.6 1664.85   137.7 1627.72   173.8    1598   216.4 1572.12   245.9 1558.69
   295.1  1559.8   311.5 1555.89   334.4 1540.09   350.8 1533.16  405.59 1530.38
  583.63  1531.1   619.7 1533.73   632.8  1540.6   698.4 1550.32   993.4 1551.25
  1036.1 1550.33  1101.6 1543.01  1114.8 1549.04  1134.4 1550.56    1800 1548.38
  2006.6  1551.9  2045.9 1555.96  2278.7 1556.49  2416.4 1560.67  2819.7 1583.47
#Mann= 4 ,-1 , 0
       0      .1       0   334.4    .033       0   632.8      .1       0
  1134.4    .055       0
#Block Obstruct= 15 ,-1
                         1282.59 1327.07 1579.56 1473.25 1484.891580.754
 1561.96 1609.951579.043 1900.75 1951.671581.449 1973.39  1984.61581.856
 2010.66 2043.821585.889 2149.32  2185.31585.515 2227.85 2282.26 1586.57
 2338.37  2387.61590.003 2423.67 2428.061591.399 2570.18 2605.721601.912
  2706.4  2731.81609.241    2732 2772.661611.765     948    1008    1600
Bank Sta=334.4,632.8
XS Rating Curve= 0 ,0
Exp/Cntr=0.3,0.1

Type RM Length L Ch R = 1 ,27028   ,404,417.4,478.7
XS GIS Cut Line= 2
     2072847.093      263337.323     2073658.942       265829.51
#Sta/Elev= 30
       0 1702.49    16.4 1686.98    45.9 1652.48    68.8  1629.3   114.7 1594.13
   150.7 1573.86   170.1 1568.25   226.1 1566.08   258.8 1555.23   291.6 1556.66
   350.6 1548.36   383.3 1538.63   393.2 1532.66  437.84 1529.43  645.87 1529.43
   671.6 1533.63   678.2 1539.23     711 1548.75   727.4 1549.57   940.3 1547.28
  1156.6 1551.43  1644.7 1545.53  1828.2 1554.88  1959.3 1552.15  2100.2 1553.28
  2195.2 1557.62  2250.9 1565.49  2499.9 1581.14  2552.3 1588.24  2621.1 1592.56
#Mann= 3 ,-1 , 0
       0      .1       0   383.3    .033       0   678.2    .065       0
#Block Obstruct= 13 ,-1
   176.9  221.971596.206  762.81  819.891578.412 1007.67 1057.811579.006
 1128.93 1186.771581.177    1227 1251.781579.425 1274.74 1319.93 1579.01
 1411.32 1438.621577.816 1524.32 1553.031576.856  1592.8 1639.261575.725
 1896.64 1925.02 1583.41 2045.18 2078.881583.009 2176.55 2373.541604.075
 2556.03 2580.961620.409
Bank Sta=383.3,678.2
XS Rating Curve= 0 ,0
Exp/Cntr=0.3,0.1

Type RM Length L Ch R = 1 ,26610   ,450.1,453.6,455
XS GIS Cut Line= 3
     2072582.611       263193.01     2072478.445      263366.621
     2073012.458      265805.205
#Sta/Elev= 30
       0 1754.75   140.4 1765.64   225.4 1768.94   238.5 1766.59   254.9 1752.81
     304 1692.04   349.9 1643.93   385.9 1616.54   438.3 1585.05   467.8 1574.04
   513.7 1567.64   549.7 1555.21   615.2  1554.7   634.9 1542.78  648.47 1539.03
   654.6 1533.26  685.35 1529.52  764.61 1529.32  893.23 1529.32     956 1532.64
  970.74    1539     992  1547.6  1008.4 1548.84  1755.3 1544.42  1902.8 1555.45
  2010.9 1551.32  2246.7 1553.36  2407.3 1563.46  2561.2 1581.62  2698.8 1586.94
#Mann= 3 , 0 , 0
       0      .1       0  648.47    .033       0  970.74    .055       0
#XS Ineff= 2 , 0
                         1878.62         1552.15
Permanent Ineff=
       F       F
#Block Obstruct= 19 ,-1
 1057.17  1121.61577.891 1131.26 1172.611577.748 1266.85 1308.951579.325
 1370.72 1421.461576.927 1485.03 1515.64 1575.65 1724.21  1803.71576.931
 1847.05 1874.661582.792  1905.6 1955.351582.967 2045.81 2082.07 1581.19
 2127.77  2174.11582.657 2195.39 2209.741582.903 2230.11 2244.991583.324
 2276.65 2312.671587.611 2336.32 2366.281591.722 2434.75 2465.331600.803
 2495.11 2533.711607.486 2548.98 2591.291612.419 2599.86 2643.621615.382
 2670.02 2698.831616.938
Bank Sta=648.47,970.74
XS Rating Curve= 0 ,0
Exp/Cntr=0.3,0.1