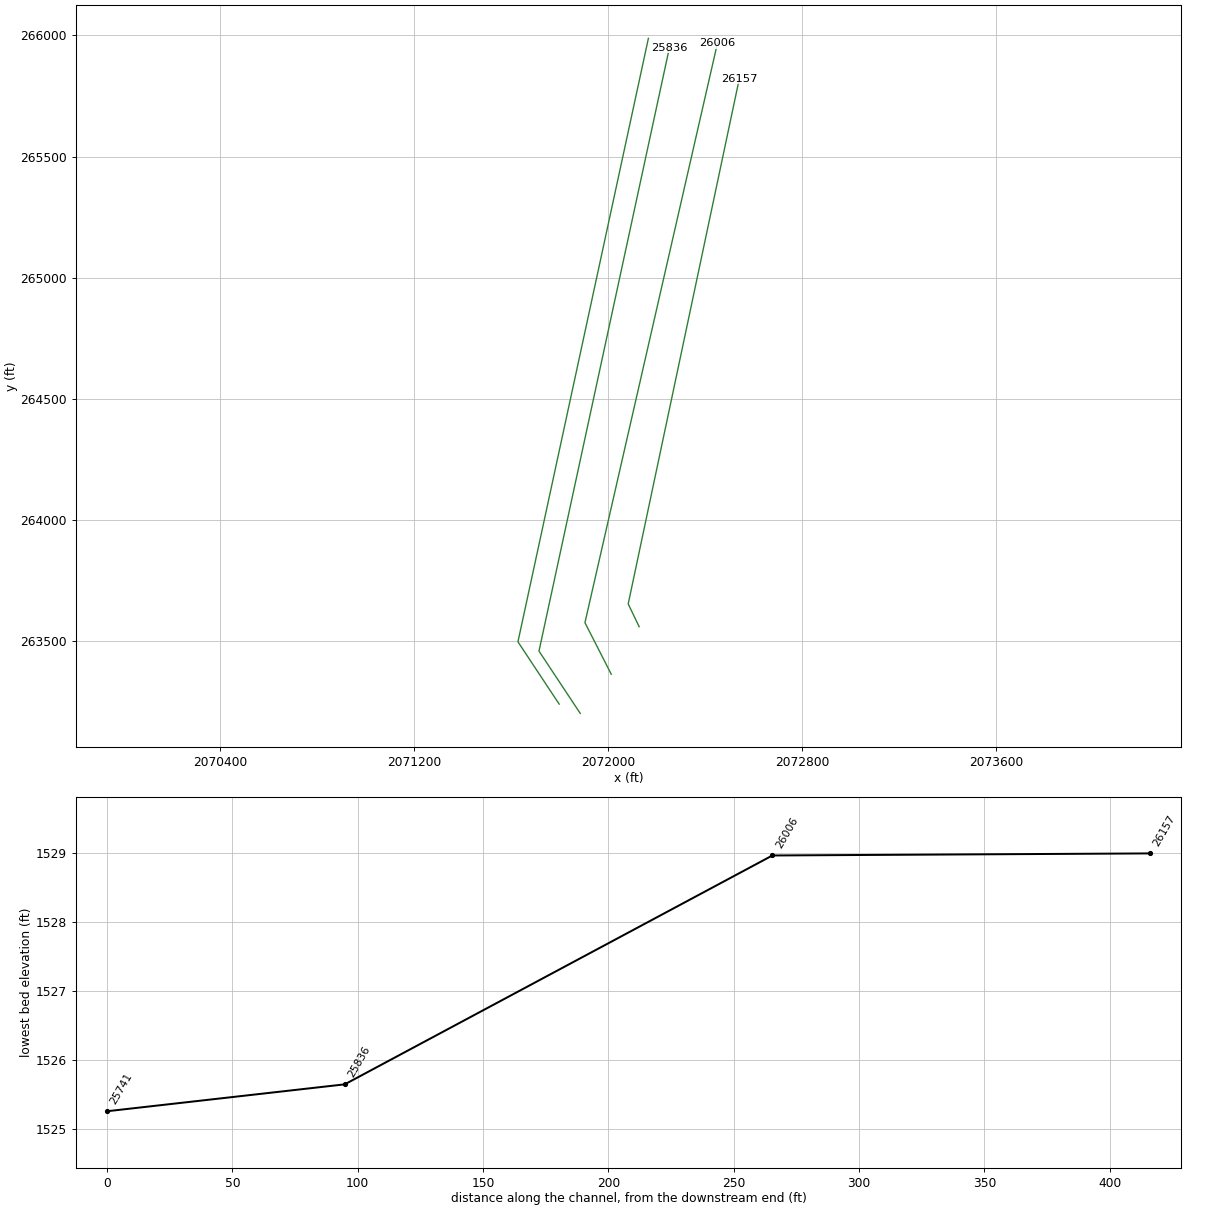
HEC-RAS study GREENBRRV1.prj: GREENBRRV1

--- GREENBRRV1.g01 (geometry) --- (continued)

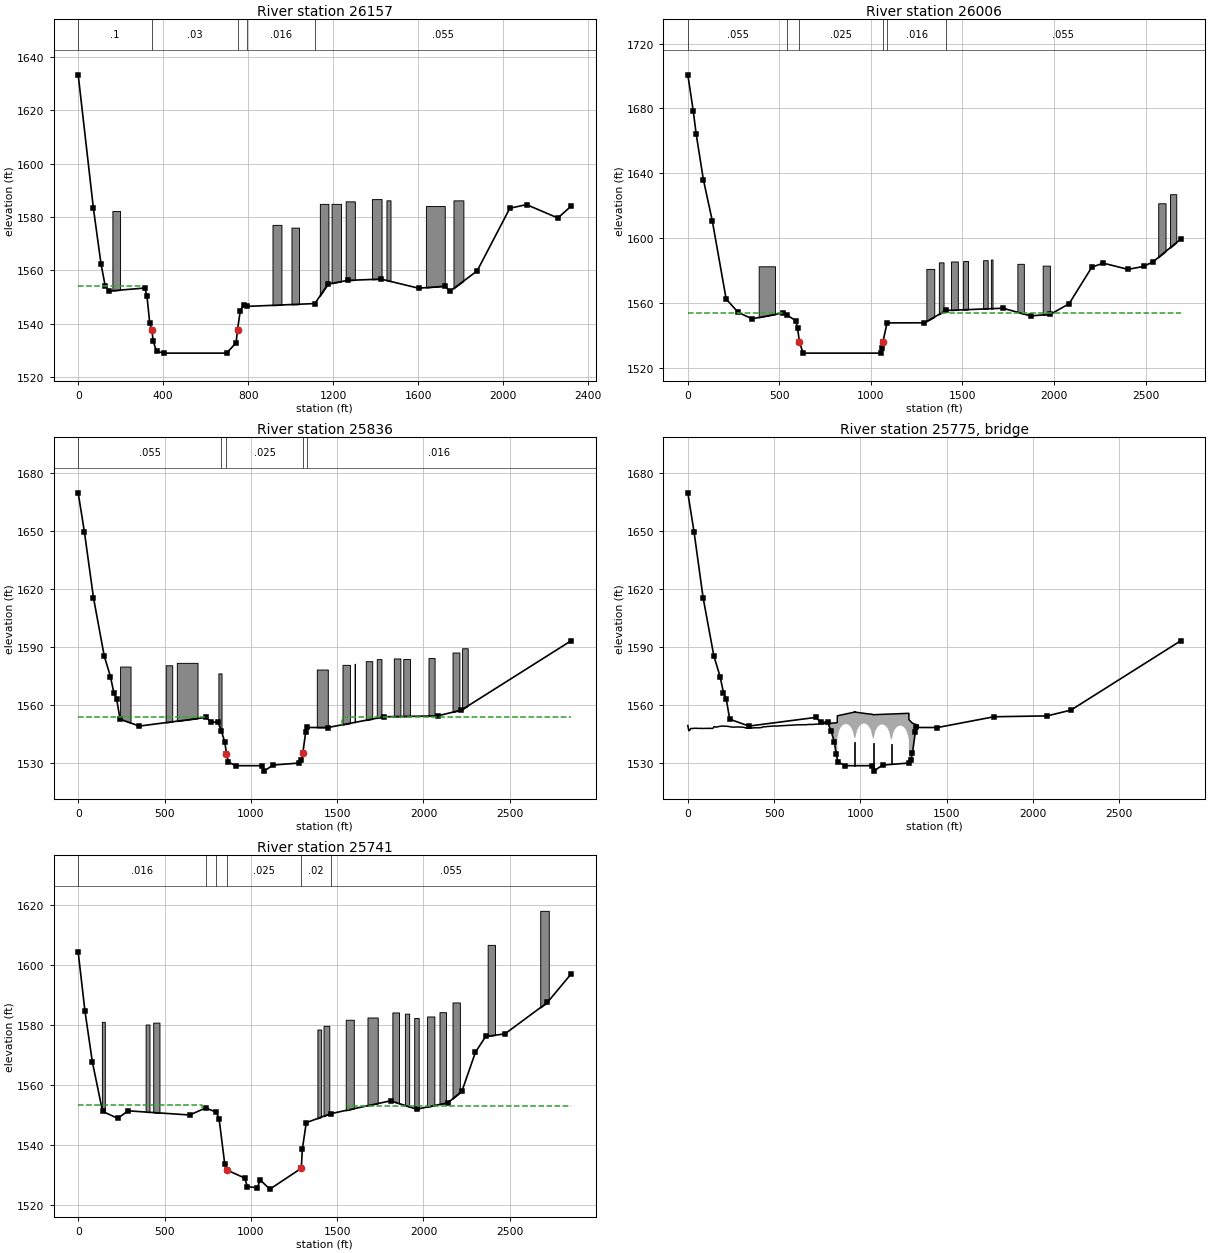
Type RM Length L Ch R = 1 ,26157   ,153.8,150.7,161.5
XS GIS Cut Line= 3
     2072128.065      263560.792     2072082.927      263654.542
      2072541.26      265821.209
#Sta/Elev= 30
       0 1633.21    71.5 1583.26   107.3 1562.45     127 1554.17   146.6 1552.27
   313.7 1553.38   323.6 1550.31   336.6 1540.22   346.5  1537.7     353 1533.47
  368.38 1529.66  405.59    1529  698.48    1529   742.9 1532.92   749.4 1537.77
   762.5 1544.91   778.9 1547.15   795.3  1546.5  1113.1 1547.56  1175.3 1554.86
    1267 1556.23  1424.3 1556.72  1601.2 1553.31  1725.7 1554.06  1748.6 1552.17
  1876.4 1559.77  2030.4 1583.26    2109 1584.61  2256.4  1579.6  2318.7 1584.06
#Mann= 5 ,-1 , 0
       0      .1       0   346.5     .03       0   749.4    .055       0
   795.3    .016       0  1113.1    .055       0
#XS Ineff= 2 , 0
          289.78 1554.04  1180.6         1553.77
Permanent Ineff=
       F       F
#Block Obstruct= 10 ,-1
  160.91  196.97 1582.22  913.94  956.091577.026 1003.24 1038.841575.995
  1136.7 1177.081584.888 1191.83 1236.291584.898 1258.23 1301.281585.834
 1381.66 1427.061586.672 1449.98 1469.051586.218 1635.65 1724.151584.071
 1765.25 1811.891586.203
Bank Sta=346.5,749.4
XS Rating Curve= 0 ,0
Exp/Cntr=0.3,0.1

Type RM Length L Ch R = 1 ,26006   ,166.9,170.6,187.1
XS GIS Cut Line= 3
     2072012.957      263364.635      2071904.45      263577.309
     2072451.325      265968.802
#Sta/Elev= 30
       0  1700.7    29.4 1678.63    45.8 1663.98      85 1636.02   134.1 1610.38
   209.3 1562.36   274.8 1554.13   350.3 1550.16   520.8 1553.79   543.8 1552.21
   589.7 1549.06   599.5 1544.45   609.4 1535.83  629.51 1528.97    1057 1528.97
  1058.7 1532.42  1065.2 1535.87  1088.2 1547.62  1291.5 1547.69  1409.6 1555.29
  1721.2 1556.68    1872 1551.94  1980.3 1552.93    2082 1559.43  2206.6 1582.05
  2268.9 1584.49  2403.4 1580.66  2488.6 1582.46  2541.1 1585.35    2692 1599.36
#Mann= 6 ,-1 , 0
       0    .055       0   543.8      .1       0   609.4    .025       0
  1065.2    .055       0  1088.2    .016       0  1409.6    .055       0
#XS Ineff= 2 , 0
          522.75 1553.78 1383.51         1553.71
Permanent Ineff=
       F       F
#Block Obstruct= 11 ,-1
     387  475.77 1582.55 1302.71 1345.711580.947 1370.82 1396.411584.974
 1437.03 1474.551585.525 1503.33 1530.351585.807 1612.59 1637.561586.324
 1654.97 1663.931586.726 1799.72 1834.961584.082 1937.93 1977.331582.963
  2568.9 2608.881621.437 2632.94 2667.351627.031
Bank Sta=609.4,1065.2
XS Rating Curve= 0 ,0
Exp/Cntr=0.3,0.1

Type RM Length L Ch R = 1 ,25836   ,93,94.8,93.2
BEGIN DESCRIPTION:
Merged DS Survey GRE022BU
END DESCRIPTION:
Node Name=MC
XS GIS Cut Line= 3
      2071885.01      263203.153     2071714.871      263460.098
     2072253.065      265949.681
#Sta/Elev= 30
       0 1669.54    36.1 1649.29    88.5 1615.34   150.8 1585.22   186.9 1574.52
   206.5 1566.24   222.9 1562.76   242.6 1552.51   354.1 1548.94   740.9 1553.42
   770.4 1550.97   809.7 1550.95   829.4 1546.38   849.1 1540.71   858.9 1534.71
   869.2 1530.41   911.5 1528.46  1066.6 1528.46  1077.4 1525.65  1127.9 1528.79
  1278.6 1529.82    1292 1531.23  1301.4 1535.14  1317.8 1545.89  1324.4 1548.22
  1445.7 1548.19  1773.5 1553.76  2081.6 1554.21  2219.3 1557.21  2855.3 1593.05
#Mann= 5 ,-1 , 0
       0    .055       0   829.4      .1       0   858.9    .025       0
  1301.4     .08       0  1324.4    .016       0
#XS Ineff= 2 , 0
          747.27 1553.45  1527.7         1553.41
Permanent Ineff=
       F       F
#Block Obstruct= 14 ,-1
  242.69  303.241579.721  507.03  544.691580.371  571.34  691.271581.633
   812.1  830.26 1576.19 1382.14 1445.781578.186 1530.92  1573.91580.602
 1601.32 1602.551581.186 1665.85 1703.211582.495  1729.5 1756.621583.563
 1828.31 1866.341583.899 1882.97 1921.721583.644 2029.07 2064.321584.111
 2168.36 2207.831586.975 2223.69 2256.181589.184
Bank Sta=858.9,1301.4
XS Rating Curve= 0 ,0
Exp/Cntr=0.3,0.1

Type RM Length L Ch R = 3 ,25775   ,,,
BEGIN DESCRIPTION:
S Monroe Street- 54025GRE020
END DESCRIPTION:
Bridge Culvert--1,0,-1,-1, 0
Deck Dist Width WeirC Skew NumUp NumDn MinLoCord MaxHiCord MaxSubmerge Is_Ogee
32.4,25,2.6,0, 149, 148, , , , 0, ,,,
       0     3.3     6.5     9.8    13.1    16.4    22.9    29.4      36    52.3
    55.6    75.2    88.3   101.4   111.2     121   127.5   130.8   140.6   143.9
   147.1   150.4   153.7   156.9   160.2   163.5   166.7   179.8   192.9   199.4
   228.9   232.1   235.4   241.9   245.2   251.8   271.4   284.4   317.2     327
   336.8   343.3   349.8   353.1   366.2   382.6   389.1   398.9   405.4   421.8
   428.3   431.6   434.9   438.1     448     461   477.4   487.2   493.7   500.3
   503.5   513.4   516.6   526.4   539.5     546   552.6   559.1   572.2   595.1
   601.6   611.5   637.6   660.5   676.9   686.7   689.9   693.2   696.5   699.8
   706.3   712.8   716.1   725.9   735.7   745.5   758.6   794.6   810.9   843.6
     860   865.4     866   875.4   885.4   895.4   905.4   915.4   925.4   935.4
   945.4   955.4   965.4   965.5   967.9   970.4   970.5   980.4   990.4  1000.4
  1010.4  1020.4  1030.4  1040.4  1050.4    1061  1070.4    1071  1072.5  1075.4
    1076  1085.4  1095.4  1105.4  1115.4  1125.4  1135.4  1145.4  1155.4  1165.4
  1175.4  1175.4  1180.5    1181  1190.5  1200.5  1210.5  1220.5  1230.5  1240.5
  1250.5  1260.5  1270.5  1280.5 1280.55  1280.6    1295    1300    1335
 1549.23 1547.52 1546.53 1546.62 1547.22 1547.71 1547.72 1547.68 1547.81 1547.81
 1547.73 1547.77 1547.69 1547.76 1547.74  1547.8 1547.76  1547.8  1547.7 1547.73
 1548.01 1548.46  1548.7  1548.6 1548.46 1548.41 1548.41 1548.73 1548.87 1548.95
 1548.85 1548.81 1548.73 1548.68 1548.62 1548.44  1548.4 1548.49 1548.39 1548.24
 1547.93 1547.95  1547.8  1547.8 1547.93 1548.02 1548.08  1548.1    1548 1548.13
 1548.23 1548.33  1548.5 1548.59 1548.58 1548.73  1548.8 1548.89    1549 1548.96
 1548.97 1548.93 1548.94 1549.04 1549.09 1549.08 1549.16 1549.16 1549.27 1549.39
 1549.47 1549.51  1549.6 1549.62 1549.67 1549.64 1549.66 1549.74 1549.78 1549.75
 1549.82 1549.76  1549.8 1549.77  1549.9 1549.93    1550 1550.21 1550.39 1550.54
 1550.61 1550.82 1554.26 1554.45 1554.64 1554.83 1555.02 1555.21  1555.4 1555.59
 1555.78 1555.97 1556.16 1556.35  1556.41556.2781556.1561556.0341555.912 1555.79
1555.6681555.5461555.4241555.302 1555.18 1555.181554.9361554.8141554.814 1554.81
1554.8431554.8761554.9091554.9421554.9751555.0081555.0411555.0741555.107 1555.14
1555.1731555.2061555.2061555.2061555.2391555.2721555.3051555.3381555.3711555.404
1555.437 1555.471555.5031555.5361555.5481552.298    1551  1550.5  1549.3
                                                                                
                                                                                
                                                                                
                                                                                
                                                                                
                                                                                
                                                                                
                                                                                
                                                                                
                 1542.731546.4771548.2331549.2761549.847 1550.031549.8471549.276
1548.2331546.477 1542.73                            15431546.7471548.5031549.547
1550.117  1550.31550.1171549.5471548.5031546.747    1543
  1542.51546.2471548.0031549.0471549.617  1549.81549.6171549.0471548.0031546.247
  1542.5                  1541.91545.6471547.4031548.4471549.017  1549.21549.017
1548.4471547.4031545.647  1541.9
       0     3.3     6.5     9.8    13.1    16.4    22.9    29.4      36    52.3
    55.6    75.2    88.3   101.4   111.2     121   127.5   130.8   140.6   143.9
   147.1   150.4   153.7   156.9   160.2   163.5   166.7   179.8   192.9   199.4
   228.9   232.1   235.4   241.9   245.2   251.8   271.4   284.4   317.2     327
   336.8   343.3   349.8   353.1   366.2   382.6   389.1   398.9   405.4   421.8
   428.3   431.6   434.9   438.1     448     461   477.4   487.2   493.7   500.3
   503.5   513.4   516.6   526.4   539.5     546   552.6   559.1   572.2   595.1
   601.6   611.5   637.6   660.5   676.9   686.7   689.9   693.2   696.5   699.8
   706.3   712.8   716.1   725.9   735.7   745.5   758.6   794.6   810.9   843.6
   855.4   855.4   855.4   865.4   875.4   885.4   895.4   905.4   915.4   925.4
   935.4   945.4   955.4   955.5   960.4   960.4   970.4   980.4   990.4  1000.4
  1010.4  1020.4  1030.4  1040.4  1050.4  1060.4    1061  1065.4    1066  1075.4
  1085.4  1095.4  1105.4  1115.4  1125.4  1135.4  1145.4  1155.4  1165.4    1166
  1170.5  1170.5  1180.5  1190.5  1200.5  1210.5  1220.5  1230.5  1240.5  1250.5
  1260.5  1270.5 1270.55  1270.6  1280.6    1295    1300    1335
 1549.23 1547.52 1546.53 1546.62 1547.22 1547.71 1547.72 1547.68 1547.81 1547.81
 1547.73 1547.77 1547.69 1547.76 1547.74  1547.8 1547.76  1547.8  1547.7 1547.73
 1548.01 1548.46  1548.7  1548.6 1548.46 1548.41 1548.41 1548.73 1548.87 1548.95
 1548.85 1548.81 1548.73 1548.68 1548.62 1548.44  1548.4 1548.49 1548.39 1548.24
 1547.93 1547.95  1547.8  1547.8 1547.93 1548.02 1548.08  1548.1    1548 1548.13
 1548.23 1548.33  1548.5 1548.59 1548.58 1548.73  1548.8 1548.89    1549 1548.96
 1548.97 1548.93 1548.94 1549.04 1549.09 1549.08 1549.16 1549.16 1549.27 1549.39
 1549.47 1549.51  1549.6 1549.62 1549.67 1549.64 1549.66 1549.74 1549.78 1549.75
 1549.82 1549.76  1549.8 1549.77  1549.9 1549.93    1550 1550.21 1550.39 1550.54
 1550.54 1553.79 1553.99 1554.19 1554.39 1554.59 1554.79 1554.99 1555.19 1555.39
 1555.59 1555.79 1555.99  1556.4  1556.41556.2781556.1561556.0341555.912 1555.79
1555.6681555.5461555.4241555.302 1555.181555.058 1554.75 1554.75 1554.75 1554.75
 1554.75 1554.75 1554.75 1554.75 1554.75 1554.75 1554.75 1554.75 1554.75 1554.81
 1554.811554.8661554.9221554.9781555.034 1555.091555.1461555.2021555.2581555.314
 1555.371555.4261555.5481552.2981552.298    1551  1550.5  1548.3
                                                                                
                                                                                
                                                                                
                                                                                
                                                                                
                                                                                
                                                                                
                                                                                
                                                                                
                 1542.731546.4771548.2331549.2761549.847 1550.031549.8471549.276
1548.2331546.477 1542.73                  1541.21544.9471546.7031547.7461548.317
  1548.51548.3171547.7461546.7031544.947  1541.2                  1542.21545.947
1547.7031548.7461549.317  1549.51549.3171548.7461547.7031545.947  1542.2
          1543.11546.8471548.6031549.6461550.217  1550.41550.2171549.6461548.603
1546.847  1543.1
Pier Skew, UpSta & Num, DnSta & Num=  ,967.9, 2 ,957.9, 2 , 0 , 0 , 0 ,,
       5       5
  1530.7  1540.7
       5       5
  1528.9  1538.9
Pier Skew, UpSta & Num, DnSta & Num=  ,1073, 2 ,1063, 2 , 0 , 0 , 0 ,,
       5       5
  1530.2  1540.2
       5       5
  1529.9  1539.9
Pier Skew, UpSta & Num, DnSta & Num=  ,1177.9, 2 ,1168, 2 , 0 , 0 , 0 ,,
       5       5
  1529.6  1539.6
       5       5
  1530.8  1540.8
BR Coef=-1 , 1 , 1 ,0.9, 0 ,,,0.8,0,1.33,0,
WSPro=,,,, 1 ,,,, 0 ,,,, 0 ,,,,-1 ,-1 ,-1 , 0 , 0 , 0 , 0 , 0
BC Design=,, 0 ,, 0 ,,0,,,,
BC HTab HWMax=0
BC HTab TWMax=0
BC HTab MaxFlow=0
BC Use User HTab Curves=0
BC User HTab FreeFlow(D)= 0

Type RM Length L Ch R = 1 ,25741   ,280,281.5,282.2
BEGIN DESCRIPTION:
Merged US Survey GRE018BD
END DESCRIPTION:
XS GIS Cut Line= 3
     2071798.204      263241.348     2071628.065      263498.292
      2072166.26      265987.876
#Sta/Elev= 30
       0 1604.28    39.3 1584.61      82 1567.73     141  1551.2   229.5 1548.87
   288.5 1551.38   645.8 1549.99   737.6 1552.32   799.9 1550.97   816.3 1548.63
   849.1 1533.53   863.4 1531.59   964.8 1528.93   979.8  1526.1  1038.2  1525.7
  1053.2 1528.34  1110.4 1525.26  1292.4 1532.22  1298.2 1538.54  1321.1 1547.43
  1462.1 1550.42  1809.5 1554.72  1960.3 1551.92  2140.6 1554.05  2222.6 1557.92
  2301.3 1570.96  2360.3 1576.18  2471.7 1577.05  2717.6 1587.52  2855.3 1597.06
#Mann= 6 ,-1 , 0
       0    .016       0   737.6     .05       0   799.9      .1       0
   863.4    .025       0  1292.4     .02       0  1462.1    .055       0
#XS Ineff= 2 , 0
          719.17 1553.31 1563.81         1552.85
Permanent Ineff=
       F       F
#Block Obstruct= 15 ,-1
  137.16   154.21581.068   390.6  412.881580.168  434.57  470.77 1580.81
 1385.55 1407.491578.502 1421.15 1454.431579.733 1549.74 1596.291581.759
 1675.68 1735.131582.518 1819.79  1858.41584.192 1892.35 1917.081583.792
 1946.35 1972.18 1582.36 2020.92 2063.071582.856 2092.78 2130.271584.292
 2168.25 2210.911587.534 2371.81 2413.971606.741 2676.27 2725.751618.096
Bank Sta=863.4,1292.4
XS Rating Curve= 0 ,0
Exp/Cntr=0.3,0.1