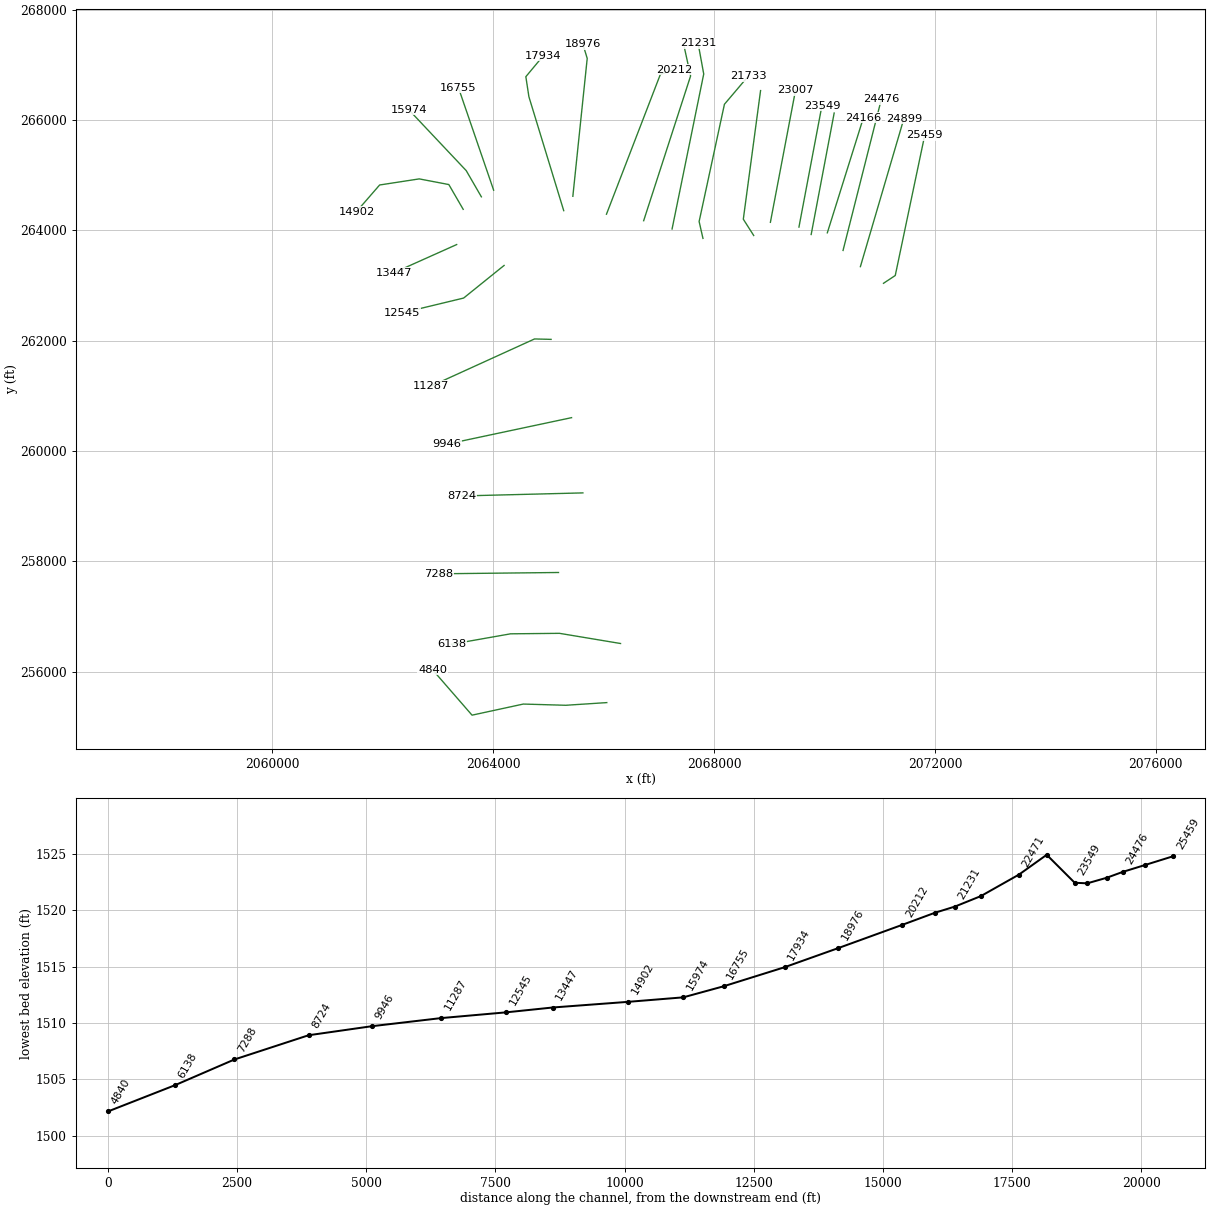
HEC-RAS study GREENBRRV1.prj: GREENBRRV1

--- GREENBRRV1.g01 (geometry) --- (continued)

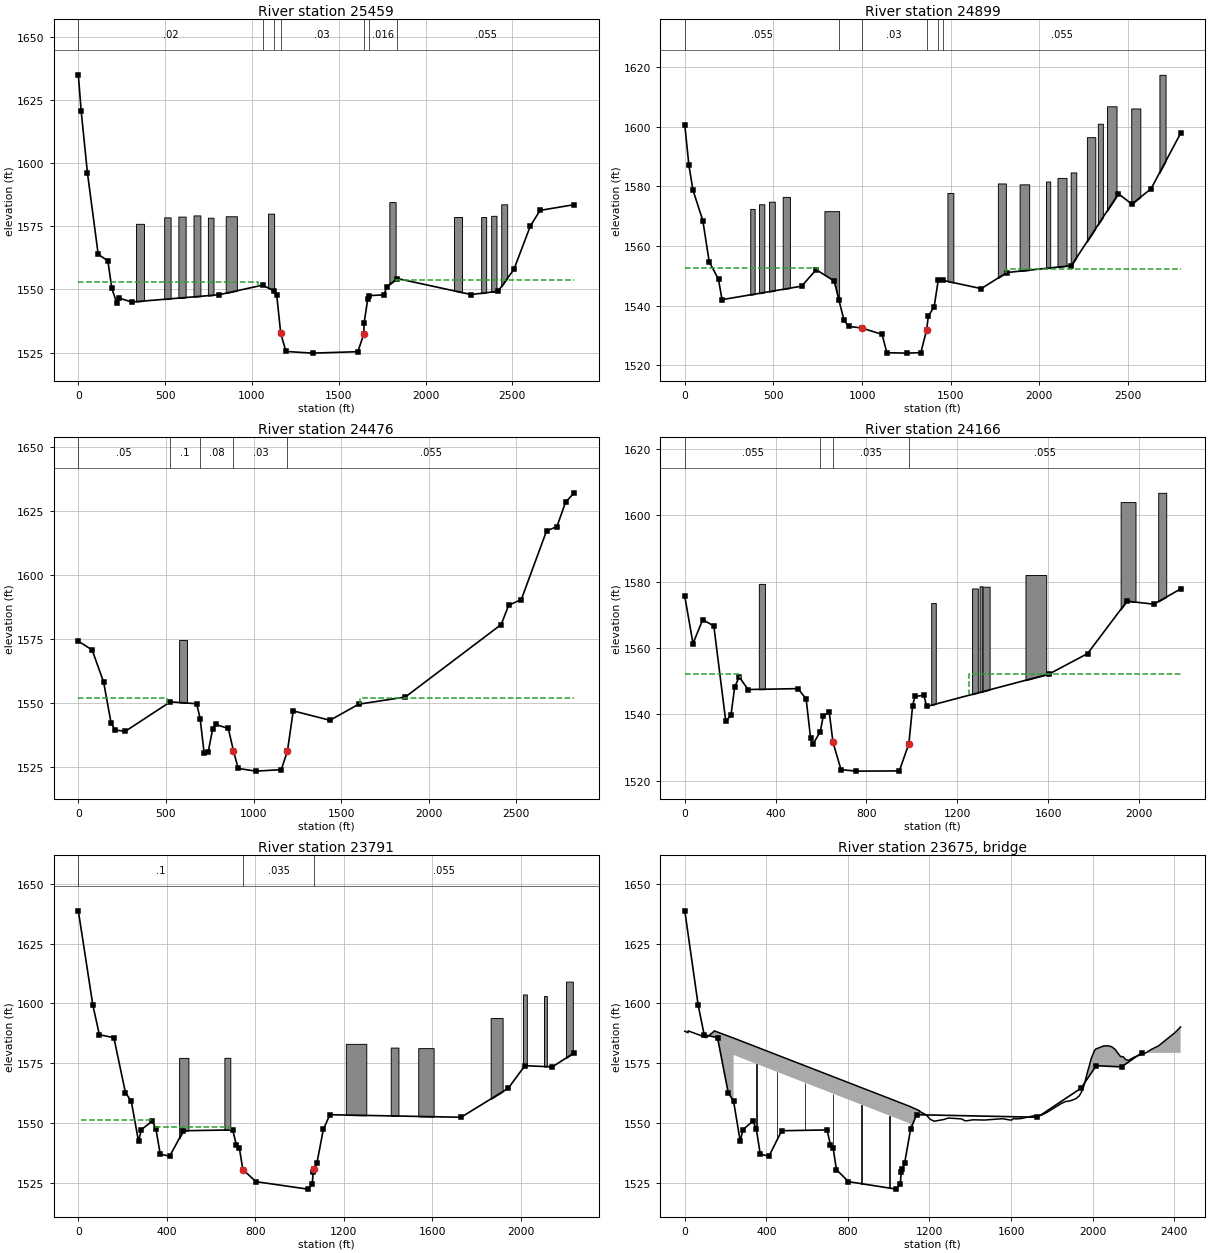
Type RM Length L Ch R = 1 ,25459   ,587.8,559.9,532.6
XS GIS Cut Line= 3
     2071069.038      263039.959     2071281.844      263180.825
     2071816.334       265726.31
#Sta/Elev= 30
       0 1634.93    16.4 1620.54    52.4 1596.14   114.5 1563.88   170.1 1561.34
     193  1550.4   222.5 1544.44   232.3 1546.64   307.6 1545.03   808.8 1547.89
    1061  1551.7  1129.8 1549.35    1143 1547.66  1165.9 1532.63 1195.97 1525.46
 1350.99  1524.8 1610.28 1525.37  1644.2  1532.3 1646.13 1536.64  1666.9 1546.05
  1676.9 1547.57  1762.1 1547.85  1775.2    1551  1837.4 1554.31  2263.3 1547.99
  2417.2 1549.27    2509  1557.9    2604 1575.13  2659.6 1581.28  2856.2 1583.55
#Mann= 7 ,-1 , 0
       0     .02       0    1061    .055       0  1129.8      .1       0
  1165.9     .03       0  1644.2     .06       0  1676.9    .016       0
  1837.4    .055       0
#XS Ineff= 2 , 0
       0 1033.81 1553.04 1825.21       0 1553.72
Permanent Ineff=
       F       F
#Block Obstruct= 12 ,-1
  332.17   378.21575.972  494.68  531.581578.531  576.28  618.111578.828
  663.46  703.131579.293   746.3  778.581578.386   849.1  913.291578.963
    1093    1128    1580 1791.61 1827.731584.573 2164.26 2210.46 1578.69
 2320.54 2349.251578.672 2378.25 2408.761579.138 2436.16 2470.36 1583.69
Bank Sta=1165.9,1644.2
XS Rating Curve= 0 ,0
Exp/Cntr=0.3,0.1

Type RM Length L Ch R = 1 ,24899   ,416.5,423.3,439.4
XS GIS Cut Line= 2
     2070650.388      263341.683     2071438.765      266025.671
#Sta/Elev= 30
       0 1600.66      23  1587.2    45.9 1578.81   101.7 1568.55   137.7 1554.72
   190.2  1548.8   209.9 1541.97   659.2  1546.5   741.2 1552.04   842.8 1548.26
   869.1 1541.89   898.6 1535.01   924.8 1532.97     997 1532.46    1113  1530.3
 1140.03 1524.13  1254.7    1524 1331.76 1524.16  1364.2 1531.76  1374.1 1536.46
  1406.9  1539.6  1429.8 1548.47  1459.4 1548.41  1672.5 1545.68  1816.8 1551.08
  2180.8  1553.4  2446.5 1577.56  2521.9 1574.09  2630.1  1579.2  2797.4 1597.87
#Mann= 6 ,-1 , 0
       0    .055       0   869.1      .1       0     997     .03       0
  1364.2     .06       0  1429.8    .016       0  1459.4    .055       0
#XS Ineff= 2 , 0
          748.93 1552.48  1809.8         1552.14
Permanent Ineff=
       F       F
#Block Obstruct= 16 ,-1
  369.27  394.081572.474  418.69  448.631574.026  475.18  507.511574.896
  552.36  592.881576.503  787.77  870.551571.711 1481.66 1515.091577.819
 1766.25 1811.431581.021 1889.06 1942.871580.721 2037.76 2061.571581.683
  2102.7 2153.621582.889 2177.16 2208.591584.723 2268.59 2315.991596.577
 2330.42 2358.611601.096 2382.29 2435.791606.954 2518.73 2570.111606.224
 2677.79 2712.37 1617.53
Bank Sta=997,1364.2
XS Rating Curve= 0 ,0
Exp/Cntr=0.3,0.1

Type RM Length L Ch R = 1 ,24476   ,326.3,310.5,290.3
XS GIS Cut Line= 2
     2070336.243      263635.066     2071030.687      266378.122
#Sta/Elev= 30
       0 1574.14    78.7 1570.69   144.3 1558.16   186.9 1542.17   209.8 1539.39
   268.9 1538.99   524.6 1550.44   675.4 1549.71   695.1 1543.91     718 1530.42
     741 1530.87   767.2 1539.98   783.6 1541.62   855.8 1540.05   885.3 1531.33
  912.31 1524.44  1013.9  1523.4 1158.17 1523.98  1193.5 1531.31  1226.3 1546.91
  1436.1 1543.25    1600 1549.53  1865.6 1552.31  2413.2 1580.63  2455.8 1588.14
    2528 1590.38  2672.2 1617.18  2731.2 1618.83  2780.4 1628.36  2829.6 1632.03
#Mann= 5 ,-1 , 0
       0     .05       0   524.6      .1       0   695.1     .08       0
   885.3     .03       0  1193.5    .055       0
#XS Ineff= 2 , 0
          505.52 1551.92 1610.01         1551.78
Permanent Ineff=
       F       F
#Block Obstruct= 1 ,-1
   575.1  619.851574.574
Bank Sta=885.3,1193.5
XS Rating Curve= 0 ,0
Exp/Cntr=0.3,0.1

Type RM Length L Ch R = 1 ,24166   ,343.5,374.4,463.5
BEGIN DESCRIPTION:
Merged DS Survey GRE012BU
END DESCRIPTION:
XS GIS Cut Line= 2
     2070051.521      263954.511     2070704.298      266037.844
#Sta/Elev= 30
       0 1575.55    36.1 1561.32    78.7  1568.5   127.8 1566.64   180.3 1537.94
   203.2 1539.67   219.6  1548.2   239.3 1551.28   278.6 1547.47   498.3 1547.74
   534.3 1544.64     554 1532.77   563.8 1530.92   596.6 1534.81   609.7 1539.51
     636 1540.67   652.3 1531.64  687.71 1523.32  755.25 1522.88  944.69 1522.94
   986.7 1531.19  1003.1 1542.58  1012.9 1545.38  1052.3 1545.73  1065.4 1542.38
    1603 1552.11  1773.4  1558.3  1947.2 1574.11  2065.2 1573.19  2183.2 1577.79
#Mann= 4 ,-1 , 0
       0    .055       0   596.6      .1       0   652.3    .035       0
   986.7    .055       0
#XS Ineff= 2 , 0
          243.35 1552.14 1251.58         1552.21
Permanent Ineff=
       F       F
#Block Obstruct= 8 ,-1
  325.91  352.751579.304 1084.92 1105.141573.515 1264.94  1290.11577.932
 1297.72 1310.531578.589 1311.16 1342.181578.448 1500.05 1591.311581.968
 1919.07 1984.49 1603.95 2084.49 2119.811606.747
Bank Sta=652.3,986.7
XS Rating Curve= 0 ,0
Exp/Cntr=0.5,0.3

Type RM Length L Ch R = 1 ,23791   ,242.6,242.6,260.3
BEGIN DESCRIPTION:
Merged DS Survey GRE012BU
END DESCRIPTION:
XS GIS Cut Line= 2
     2069758.986      263924.129     2070175.653      266125.517
#Sta/Elev= 30
       0 1638.74    65.5 1599.36      95 1586.94   160.5 1585.71   212.9 1562.72
   239.1 1559.19   271.9 1542.41     285 1547.26   334.1 1550.84   350.5 1547.61
   370.1 1537.02   412.7 1536.14     475  1546.8   697.7 1547.14   714.1 1540.86
   727.2 1539.72   743.6 1530.55   802.6 1525.51    1037 1522.39  1056.8 1524.42
  1061.3 1529.36 1066.75  1530.6 1078.08 1533.25  1107.1 1547.34  1136.6  1553.5
  1729.5 1552.44  1942.4 1564.54  2017.7 1573.98  2142.2 1573.51  2240.5 1579.37
#Mann= 3 ,-1 , 0
       0      .1       0   743.6    .035       0 1066.75    .055       0
#XS Ineff= 3 ,-1
   14.22  334.241551.419    1190  2240.5 1551.37  345.41   685.61548.345
Permanent Ineff=
       F       F       F
#Block Obstruct= 9 ,-1
  455.41  497.52 1577.26  660.04  686.69 1577.29 1208.86 1301.111583.133
 1411.64 1446.531581.566 1535.93 1605.371581.337 1863.23 1917.311593.911
 2009.08 2026.621603.773 2104.41 2117.021603.103 2203.38 2234.541609.148
Bank Sta=743.6,1066.75
XS Rating Curve= 0 ,0
Exp/Cntr=0.5,0.3

Type RM Length L Ch R = 3 ,23675   ,,,
BEGIN DESCRIPTION:
Howell Street- 54025GRE010
END DESCRIPTION:
Bridge Culvert--1,0,-1,-1, 0
Deck Dist Width WeirC Skew NumUp NumDn MinLoCord MaxHiCord MaxSubmerge Is_Ogee
75,46,2.6,0, 60, 60, , , , 0, ,,,
       0   16.07   16.17  106.16  143.67  143.77  239.13  239.23 1103.47 1103.57
 1150.31 1150.41    1164  1183.7  1203.3    1223  1272.1  1291.7  1357.3  1373.6
  1383.5  1412.9  1468.6  1557.1  1599.6  1606.2  1612.7  1622.6  1648.8  1717.5
  1730.6  1737.2  1750.3  1773.2  1848.6  1868.2  1891.1  1917.3  1933.7  1943.5
  1956.7  1976.3  1982.9  1992.7  2009.1  2015.6  2054.9  2077.8  2094.2  2110.6
  2136.8  2149.9    2163  2176.1  2205.6  2261.3  2287.5  2323.5  2405.4  2431.6
  1588.4 1587.79 1588.57 1585.72 1588.38 1588.57 1585.54 1585.54 1556.98 1556.98
 1555.17    1555  1554.3 1553.47 1551.57 1550.78 1551.53 1552.11 1551.75 1550.98
 1550.98 1551.38 1551.27 1551.83 1551.24 1551.44 1551.97 1551.74 1551.89 1553.15
 1552.34 1553.21 1553.38 1554.34  1558.3 1559.01 1559.32 1560.16  1561.3 1562.65
 1565.36 1571.83  1573.7  1576.9  1580.3 1580.97 1582.26 1582.29  1581.9 1580.76
 1577.82 1577.75 1576.51 1576.26 1577.63 1579.36 1580.79 1582.31 1587.93  1590.2
                                                         1578.49 1549.84
                                                                                
                                                                                
                                                                                
                                                                                
                                                                                
    46.5   62.57   84.57   84.67  179.97  180.07 1044.62 1044.72 1091.21 1091.31
  1104.9  1124.6  1144.2  1163.9    1213  1232.6  1298.2  1314.5  1324.4  1353.8
  1409.5  1448.8  1468.5    1498  1540.5  1547.1  1553.6  1563.5  1589.7  1658.4
  1671.5  1678.1  1691.2  1714.1  1789.5  1809.1    1832  1858.2  1874.6  1884.4
  1897.6  1917.2  1923.8  1933.6    1950  1956.5  1995.8  2018.7  2035.1  2051.5
  2077.7  2090.8  2103.9    2117  2146.5  2202.2  2228.4  2264.4  2346.3  2372.5
  1588.4 1587.79 1588.38 1588.57 1585.55 1585.55 1556.97 1556.97 1555.17    1555
  1554.3 1553.47 1551.57 1550.78 1551.53 1552.11 1551.75 1550.98 1550.98 1551.38
 1551.27  1551.6 1551.48 1551.83 1551.24 1551.44 1551.97 1551.74 1551.89 1553.15
 1552.34 1553.21 1553.38 1554.34  1558.3 1559.01 1559.32 1560.16  1561.3 1562.65
 1565.36 1571.83  1573.7  1576.9  1580.3 1580.97 1582.26 1582.29  1581.9 1580.76
 1577.82 1577.75 1576.51 1576.26 1577.63 1579.36 1580.79 1582.31 1587.93  1590.2
                                         1578.58 1550.11
                                                                                
                                                                                
                                                                                
                                                                                
                                                                                
Pier Skew, UpSta & Num, DnSta & Num=  ,350.5, 2 ,234.6, 2 , 0 , 0 , 0 ,,
       3       3
  1546.4  1574.7
       3       3
  1546.4    1579
Pier Skew, UpSta & Num, DnSta & Num=  ,452, 2 ,350, 2 , 0 , 0 , 0 ,,
       3       3
  1536.6  1571.4
       3       3
  1536.6    1574
Pier Skew, UpSta & Num, DnSta & Num=  ,589.6, 2 ,470, 2 , 0 , 0 , 0 ,,
       3       3
  1547.6  1566.8
       3       3
  1547.6    1570
Pier Skew, UpSta & Num, DnSta & Num=  ,727.4, 2 ,600, 2 , 0 , 0 , 0 ,,
       3       3
  1539.8  1562.2
       3       3
  1539.8    1566
Pier Skew, UpSta & Num, DnSta & Num=  ,866, 2 ,735, 2 , 0 , 0 , 0 ,,
       3       3
  1525.6  1557.7
       3       3
  1525.6    1562
Pier Skew, UpSta & Num, DnSta & Num=  ,1004, 2 ,872, 2 , 0 , 0 , 0 ,,
       3       3
  1524.3  1553.1
       3       3
  1524.3    1556
BR Coef=-1 , 1 , 0 ,, 0 ,,,0.8,-1,1.33,1,
WSPro=,,,, 1 ,,,, 0 ,,,, 0 ,,,,-1 ,-1 ,-1 , 0 , 0 , 0 , 0 , 0
BC Design=,, 0 ,, 0 ,,0,,,,
BC HTab HWMax=0
BC HTab TWMax=0
BC HTab MaxFlow=0
BC Use User HTab Curves=0
BC User HTab FreeFlow(D)= 0

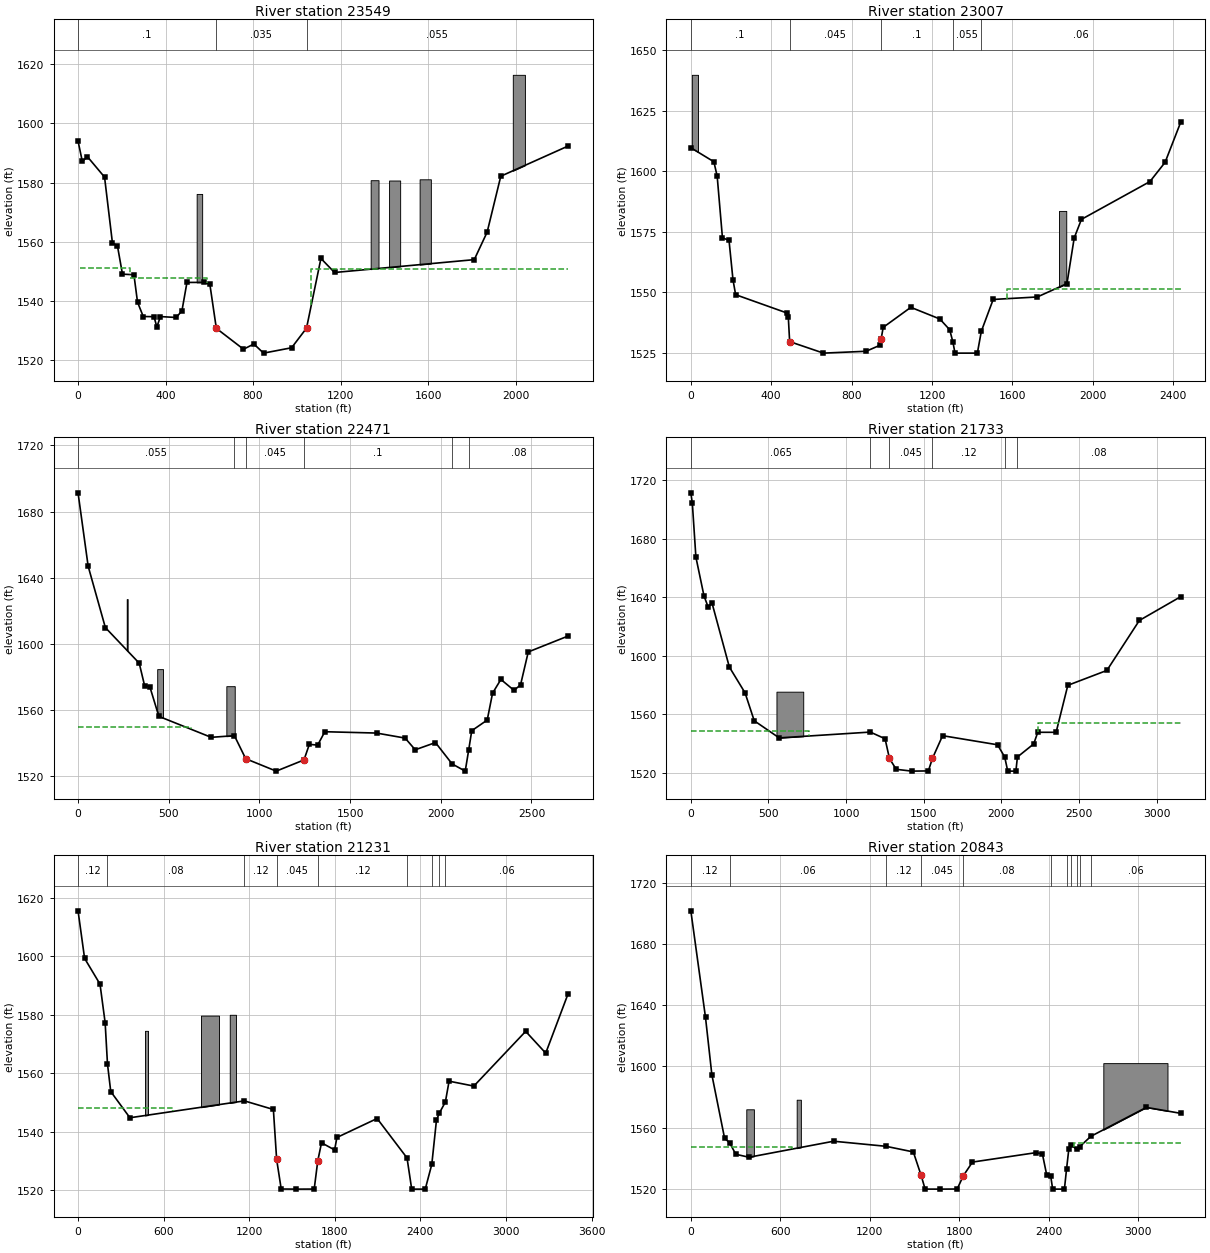
Type RM Length L Ch R = 1 ,23549   ,540.4,542,549.9
BEGIN DESCRIPTION:
Merged US Survey GRE008BD
END DESCRIPTION:
Node Name=MB
XS GIS Cut Line= 2
     2069537.632      264058.677     2069954.298      266260.066
#Sta/Elev= 30
       0 1594.05    19.6 1587.16    42.6  1588.8   121.2 1581.88   157.2 1559.65
   180.2 1558.63   203.1 1549.11   255.5 1548.91   271.9 1539.66   298.1  1534.8
   347.2 1534.75   360.3 1531.29   376.7 1534.78   448.8 1534.48     475 1536.74
   497.9 1546.31   576.5 1546.33   602.7 1545.65   632.2 1530.81   756.4 1523.76
   803.8 1525.52   848.1 1522.44   976.2 1524.25 1044.48 1530.87  1110.4 1554.41
  1172.6 1549.67  1811.4 1554.01  1870.3 1563.31  1932.6 1582.18  2240.5 1592.38
#Mann= 3 ,-1 , 0
       0      .1       0   632.2    .035       0 1044.48    .055       0
#XS Ineff= 3 ,-1
    9.31   239.31551.109   239.3  590.29 1547.92    1066  2240.5    1551
Permanent Ineff=
       F       F       F
#Block Obstruct= 5 ,-1
  542.27   567.41576.199 1337.79 1373.661580.836 1421.88 1472.591580.732
 1561.55 1612.941581.143 1987.57 2042.951616.422
Bank Sta=632.2,1044.48
XS Rating Curve= 0 ,0
Exp/Cntr=0.5,0.3

Type RM Length L Ch R = 1 ,23007   ,520.1,535.1,558.5
Node Name=GB
XS GIS Cut Line= 2
     2069020.427      264144.993     2069476.156      266540.827
#Sta/Elev= 30
       0  1609.8   114.7    1604   131.1 1598.03   157.3  1572.6   190.1 1571.49
   209.8 1555.23   222.9 1549.07   478.6  1541.5   485.1 1539.78   491.7 1529.68
   660.1 1524.92   872.2 1525.69   940.8 1528.16   947.3 1530.88   957.2 1535.56
  1094.8 1543.85  1239.1 1539.03  1288.2 1534.58  1304.6 1529.35  1314.5 1524.92
  1425.9 1524.92  1445.6 1533.95  1504.6  1547.1  1724.2 1548.13  1871.7 1553.65
  1907.8 1572.53  1943.8  1580.2  2284.7 1595.82  2360.1 1603.77  2438.8 1620.56
#Mann= 5 ,-1 , 0
       0      .1       0   491.7    .045       0   947.3      .1       0
  1304.6    .055       0  1445.6     .06       0
#XS Ineff= 2 , 0
                         1572.97          1551.4
Permanent Ineff=
       F       F
#Block Obstruct= 2 ,-1
    5.03   35.821639.925 1832.17 1868.191583.685
Bank Sta=491.7,947.3
XS Rating Curve= 0 ,0
Exp/Cntr=0.3,0.1

Type RM Length L Ch R = 1 ,22471   ,826.5,738,692.4
XS GIS Cut Line= 3
     2068718.187      263905.899     2068529.975      264201.417
     2068842.475      266532.146
#Sta/Elev= 30
       0 1691.39    55.7 1647.04   150.6 1609.94   337.3 1588.42   366.8 1574.88
   396.3    1574   445.5 1556.28   734.1  1543.6     862 1544.61   924.3 1530.68
  1092.7 1523.17  1245.7 1529.94  1275.2 1539.34  1321.2 1538.91  1360.5 1546.99
  1645.9 1546.18  1803.3 1543.14    1859 1536.07  1970.6 1540.43  2062.4 1527.52
  2134.6 1523.17  2154.2 1536.21  2170.6  1547.6  2255.9 1554.04  2285.4 1570.29
  2331.3 1578.59  2403.5 1572.02  2439.6 1575.28  2482.2 1595.22    2702 1604.84
#Mann= 6 ,-1 , 0
       0    .055       0     862     .08       0   924.3    .045       0
  1245.7      .1       0  2062.4     .05       0  2154.2     .08       0
#XS Ineff= 2 , 0
           625.1 1549.84
Permanent Ineff=
       F       F
#Block Obstruct= 3 ,-1
  268.35   273.61627.166  436.38  468.571584.823  817.66   863.91574.519
Bank Sta=924.3,1245.7
XS Rating Curve= 0 ,0
Exp/Cntr=0.3,0.1

Type RM Length L Ch R = 1 ,21733   ,514.2,502.8,507.2
XS GIS Cut Line= 4
      2067799.13      263853.616     2067729.686      264159.172
     2068188.019      266284.172     2068620.965      266794.788
#Sta/Elev= 30
       0 1711.39     9.8 1704.12    32.6 1667.48    84.9 1640.92     111 1633.54
   137.1 1635.85   248.1 1592.37   349.4 1574.71   408.4 1555.67   569.1 1543.97
    1156 1547.94  1251.1 1543.38 1279.37 1529.89 1322.86  1522.5  1423.1 1521.26
 1530.04  1521.4    1556  1529.9  1621.6 1545.48  1975.7 1539.26  2021.6 1530.94
  2041.3 1521.26  2093.8 1521.26  2103.6 1530.91  2208.5 1539.85  2234.7 1547.79
  2352.8 1547.78  2428.2 1579.88  2679.9 1590.06  2888.9 1624.18  3156.7 1640.52
#Mann= 6 ,-1 , 0
       0    .065       0    1156      .1       0 1279.37    .045       0
    1556     .12       0  2021.6     .05       0  2103.6     .08       0
#XS Ineff= 2 , 0
          759.29 1548.45 2236.69         1553.99
Permanent Ineff=
       F       F
#Block Obstruct= 1 ,-1
  551.57  724.02 1575.54
Bank Sta=1279.37,1556
XS Rating Curve= 0 ,0
Exp/Cntr=0.3,0.1

Type RM Length L Ch R = 1 ,21231   ,391.8,387.4,343.2
XS GIS Cut Line= 3
     2067239.832      264023.912     2067813.019      266832.783
     2067710.589      267392.679
#Sta/Elev= 30
       0 1615.51    45.9 1599.25     154 1590.44     190 1577.24   206.4 1563.11
   229.3  1553.7   363.7 1544.74  1166.4 1550.51  1369.5 1547.57  1392.4 1530.47
  1424.4 1520.37  1530.3 1520.33 1655.74 1520.35  1680.7    1530    1707 1536.18
  1798.7 1533.74  1815.1    1538  2096.8 1544.48  2306.5    1531  2339.3 1520.33
  2434.3 1520.33  2480.2 1528.82  2512.9 1543.92  2532.6  1546.3  2575.2  1550.1
  2601.4 1557.25    2775 1555.57  3138.3 1574.29  3278.9 1566.84    3436 1587.18
#Mann= 9 ,-1 , 0
       0     .12       0   206.4     .08       0  1166.4     .12       0
  1392.4    .045       0  1680.7     .12       0  2306.5    .045       0
  2480.2     .12       0  2532.6    .016       0  2575.2     .06       0
#XS Ineff= 2 , 0
          667.51 1548.06
Permanent Ineff=
       F       F
#Block Obstruct= 3 ,-1
  469.24  490.471574.464   861.8  988.141579.675 1063.63 1107.291579.955
Bank Sta=1392.4,1680.7
XS Rating Curve= 0 ,0
Exp/Cntr=0.3,0.1

Type RM Length L Ch R = 1 ,20843   ,597.4,630.9,572.8
XS GIS Cut Line= 3
     2066725.345      264173.929     2067575.114      266796.903
     2067462.267      267313.396
#Sta/Elev= 30
       0 1701.69    98.4 1632.01     141 1594.56   226.2 1553.09   260.1 1550.04
   301.6 1542.56   390.1 1540.62   957.3 1551.09  1307.9 1547.78  1491.7 1544.09
  1544.2 1528.74 1570.74  1519.8  1667.9 1519.78  1785.7 1519.85 1827.61 1528.62
  1888.4 1537.46  2314.6 1543.63  2357.2 1542.75  2386.7 1528.77  2412.7 1528.41
  2426.1 1519.78  2504.8 1519.78  2519.5 1533.23  2534.3 1545.93  2549.5 1548.92
  2586.7 1545.72  2606.4 1547.41  2681.8 1554.28  3054.2 1573.21  3285.9  1569.3
#Mann= 11 ,-1 , 0
       0     .12       0   260.1     .06       0  1307.9     .12       0
  1544.2    .045       0 1827.61     .08       0  2412.7    .045       0
  2519.5     .08       0  2549.5    .016       0  2586.7     .06       0
  2606.4    .016       0  2681.8     .06       0
#XS Ineff= 2 , 0
          675.49 1547.62 2570.37         1550.22
Permanent Ineff=
       F       F
#Block Obstruct= 3 ,-1
  371.82  422.81 1571.96  709.75  737.811578.215 2765.61  3195.91602.132
Bank Sta=1544.2,1827.61
XS Rating Curve= 0 ,0
Exp/Cntr=0.3,0.1

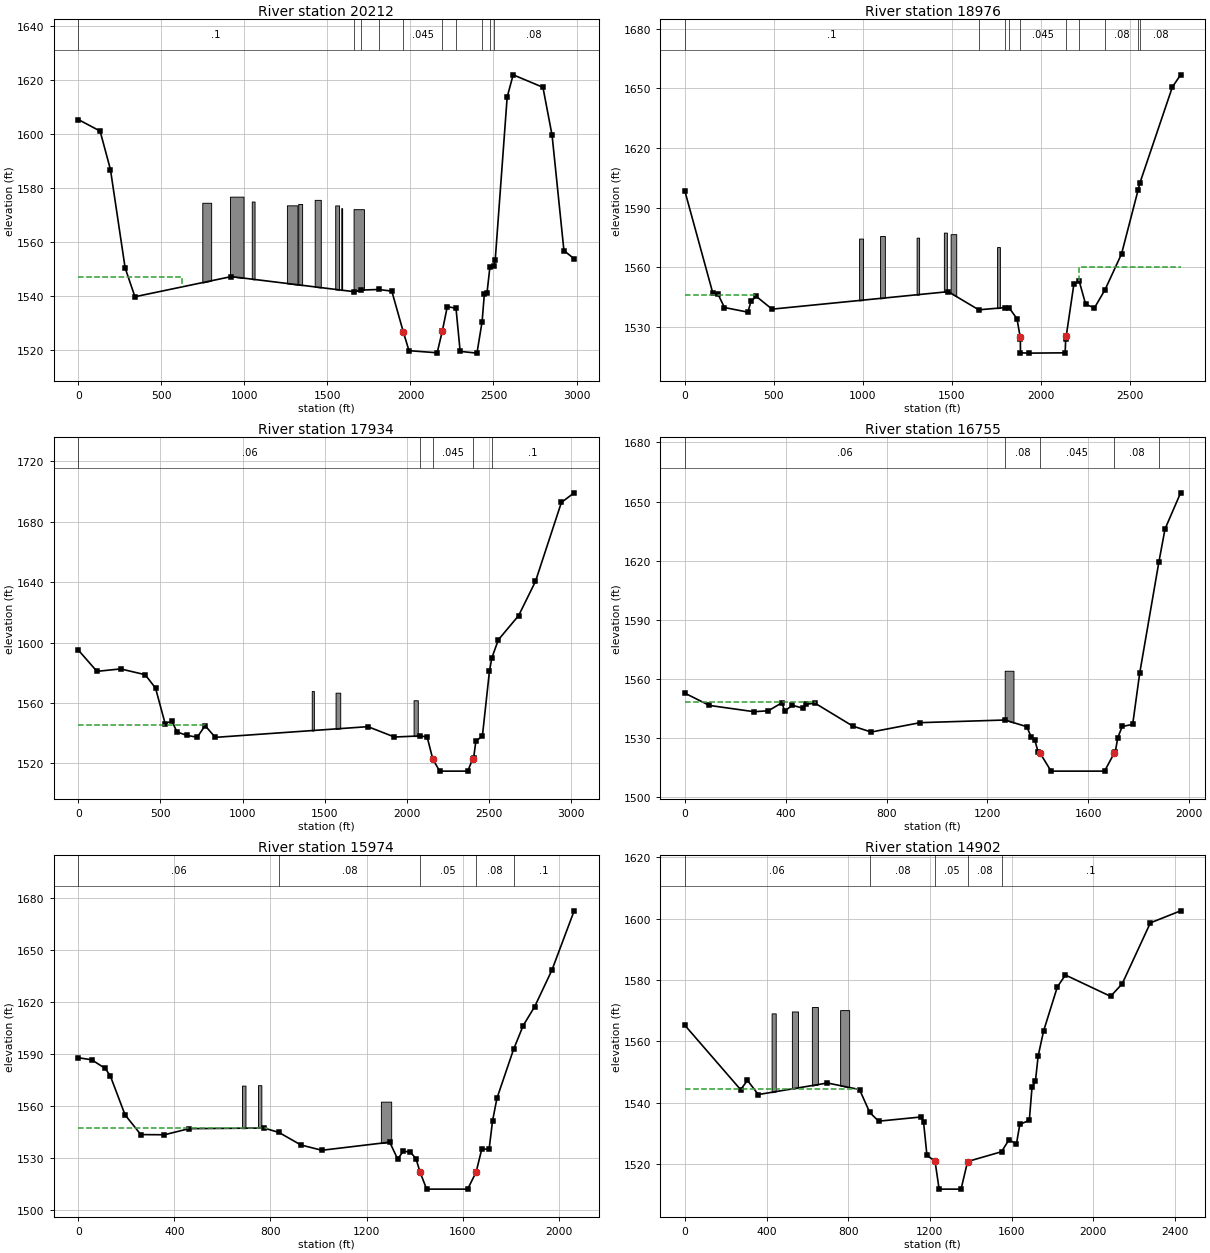
Type RM Length L Ch R = 1 ,20212   ,1133.5,1237.8,1267.6
Node Name=A
XS GIS Cut Line= 3
     2066051.734      264291.984     2067028.239      266827.285
     2067284.315       266909.75
#Sta/Elev= 30
       0 1605.36   131.1 1601.08   193.4 1586.81   281.8 1550.32   340.8 1539.63
   920.9  1547.1  1659.9 1541.51  1704.8  1542.1  1807.8 1542.32  1887.7 1541.71
  1956.5  1526.7 1991.17 1519.62 2161.01 1518.84  2192.5 1527.07    2222 1535.99
  2274.4 1535.32 2299.33 1519.36 2400.57 1518.71  2431.6 1530.41  2444.8 1540.48
  2461.2  1541.1  2478.4 1550.59  2502.1 1550.99  2510.4 1553.18  2582.5 1613.71
  2618.5 1621.95  2797.9 1617.32    2853  1599.5  2924.3 1556.74  2985.9 1553.72
#Mann= 10 ,-1 , 0
       0      .1       0  1659.9    .016       0  1704.8     .06       0
  1807.8     .12       0  1956.5    .045       0  2192.5      .1       0
  2274.4    .045       0  2431.6     .08       0  2478.4    .016       0
  2502.1     .08       0
#XS Ineff= 2 , 0
          623.15 1546.88
Permanent Ineff=
       F       F
#Block Obstruct= 9 ,-1
  746.51  799.881574.491  913.06  994.791576.758 1044.43 1061.221574.947
 1256.06 1319.751573.534 1324.22 1347.631574.045 1423.42 1460.091575.569
 1546.93 1570.211573.499  1583.4 1588.751572.498 1657.52 1719.971572.112
Bank Sta=1956.5,2192.5
XS Rating Curve= 0 ,0
Exp/Cntr(USF)=0,0
Exp/Cntr=0.3,0.1

Type RM Length L Ch R = 1 ,18976   ,1041.4,1041.4,1041.4
Node Name=[ei]
XS GIS Cut Line= 3
2065442.81341369264616.5751283792065702.84159725267115.059743186
2065623.94342881267375.118618466
#Sta/Elev= 30
       0 1598.42   157.2 1546.91   186.4 1546.35   222.7 1539.63   354.6 1537.28
   371.1 1542.69   400.8 1545.28   489.8 1538.81  1479.1 1547.62  1650.2 1538.48
  1795.7 1539.58    1822 1539.35  1864.9 1533.97  1882.5 1525.02  1883.8 1523.79
  1884.7  1516.8 1931.06 1516.65  2135.3  1516.8  2138.6 1523.75  2141.9 1525.45
  2184.3 1551.33  2213.7 1553.11  2250.7 1541.24  2300.2 1539.47  2359.5 1548.62
  2451.9 1566.62  2545.5    1599  2555.8 1602.57  2737.4 1650.72 2783.74 1656.87
#Mann= 10 ,-1 , 0
       0      .1       0  1650.2    .016       0  1795.7     .06       0
    1822     .12       0  1882.5    .045       0  2141.9      .1       0
  2213.7    .045       0  2359.5     .08       0  2545.5    .016       0
  2555.8     .08       0
#XS Ineff= 2 , 0
          400.85 1545.71 2210.75         1560.18
Permanent Ineff=
       F       F
#Block Obstruct= 6 ,-1
  978.52 1000.841574.369 1096.34 1123.171575.649 1301.51 1315.421574.822
 1454.51 1471.351577.363 1492.55 1523.87 1576.59 1753.18 1769.031570.093
Bank Sta=1882.5,2141.9
XS Rating Curve= 0 ,0
Exp/Cntr(USF)=0,0
Exp/Cntr=0.3,0.1

Type RM Length L Ch R = 1 ,17934   ,1179.6,1179.6,1179.6
BEGIN DESCRIPTION:
EH
END DESCRIPTION:
Node Name=[eh]
XS GIS Cut Line= 4
2065277.30557406 264356.486299542064646.67258076266421.412121366
2064591.46158278266783.9871183812064906.77601641267162.300287966
#Sta/Elev= 30
       0 1595.09  113.19    1581  257.27 1582.62  407.06 1578.78  469.95  1569.9
  528.27 1546.44  569.44 1548.11  600.31 1540.92  658.63 1538.67  723.81 1537.39
  771.83 1545.08  833.58  1537.3 1763.04 1544.39 1924.46 1537.53 2082.25 1538.27
 2123.42 1537.55 2157.73 1522.91 2199.73 1514.95 2370.57 1514.95 2400.03 1522.88
 2406.67 1523.87 2419.94 1534.78 2459.77 1538.19 2502.65  1581.1 2517.05 1589.84
 2556.66 1601.87 2680.29 1617.92 2782.77 1640.53 2940.51 1692.81 3018.32 1699.19
#Mann= 5 ,-1 , 0
       0     .06       0 2082.25     .08       0 2157.73    .045       0
 2400.03     .08       0 2517.05      .1       0
#XS Ineff= 2 , 0
          773.92 1545.45
Permanent Ineff=
       F       F
#Block Obstruct= 3 ,-1
 1420.95 1433.821567.992 1565.93 1594.311566.875 2040.84 2066.361561.875
Bank Sta=2157.73,2400.03
XS Rating Curve= 0 ,0
Exp/Cntr(USF)=0,0
Exp/Cntr=0.3,0.1

Type RM Length L Ch R = 1 ,16755   ,780.5,780.5,780.5
BEGIN DESCRIPTION:
EG
END DESCRIPTION:
Node Name=[eg]
XS GIS Cut Line= 2
2064008.34625566264726.8571622092063369.86663854 266586.86508275
#Sta/Elev= 30
       0 1552.83    97.5 1546.59   274.4 1543.41  331.14 1543.87   385.4 1547.96
  395.81 1543.73  427.03 1546.66  468.65 1545.18  480.91 1547.23  517.06 1547.69
  666.37  1536.1  739.21 1533.09  933.46 1537.85 1269.93 1539.19 1356.65 1535.79
 1373.99 1530.51 1387.87  1529.2 1401.74 1522.73 1408.68  1522.5 1452.73 1513.26
 1664.96 1513.26 1703.53  1522.5 1706.99 1522.81  1717.4 1530.25 1734.74 1535.91
 1776.37 1536.97 1804.12 1562.88 1880.43 1619.44 1904.71 1636.13 1966.54 1654.45
#Mann= 5 ,-1 , 0
       0     .06       0 1269.93     .08       0 1408.68    .045       0
 1703.53     .08       0 1880.43      .1       0
#XS Ineff= 2 , 0
          516.77 1548.38
Permanent Ineff=
       F       F
#Block Obstruct= 1 ,-1
 1268.85 1303.511564.182
Bank Sta=1408.68,1703.53
XS Rating Curve= 0 ,0
Exp/Cntr(USF)=0,0
Exp/Cntr=0.3,0.1

Type RM Length L Ch R = 1 ,15974   ,1071.6,1071.6,1071.6
BEGIN DESCRIPTION:
EF
END DESCRIPTION:
Node Name=[ef]
XS GIS Cut Line= 3
2063785.88032889264606.9726675392063511.77359234265081.517893414
2062471.37379489266184.911215938
#Sta/Elev= 30
       0 1588.02    55.5 1586.85  112.33 1581.83  133.27 1577.52  194.45 1555.11
  260.09 1543.72   358.6 1543.62  461.02 1547.15  773.51 1547.49  835.29 1544.95
  926.83 1537.73    1014 1534.68 1296.59 1539.35 1329.64  1529.6 1352.85 1534.07
 1382.27 1533.73 1406.23 1529.71 1422.86 1522.12  1450.2 1512.28 1620.99 1512.28
 1656.42 1522.12  1680.1 1535.51 1710.27 1535.18 1724.98 1551.78 1743.01 1564.65
 1812.39  1592.9 1852.49  1606.6 1900.32 1617.52 1972.05 1638.57 2064.57 1672.72
#Mann= 5 ,-1 , 0
       0     .06       0  835.29     .08       0 1422.86     .05       0
 1656.42     .08       0 1812.39      .1       0
#XS Ineff= 2 , 0
          785.59  1547.4
Permanent Ineff=
       F       F
#Block Obstruct= 3 ,-1
681.3069695.97691571.959748.1069762.06691572.1991259.7971302.6771562.709
Bank Sta=1422.86,1656.42
XS Rating Curve= 0 ,0
Exp/Cntr=0.3,0.1

Type RM Length L Ch R = 1 ,14902   ,1455.4,1455.4,1455.4
BEGIN DESCRIPTION:
EE
END DESCRIPTION:
Node Name=[ee]
XS GIS Cut Line= 5
 2063456.6602215264380.0697436982063196.55171023264829.275269307
2062660.58805982264931.7073528952061943.41081776264821.397135736
 2061525.6438915264340.580211619
#Sta/Elev= 30
       0 1565.29  273.17  1544.3  306.79  1547.3  359.91  1542.7  698.41 1546.46
   855.4 1544.32  905.51 1536.85  948.93 1534.02 1155.45 1535.38 1168.73 1533.81
 1185.33 1522.93 1225.16 1520.94 1245.01 1511.88 1352.45 1511.88 1384.49 1520.88
 1550.46 1524.06 1586.98 1527.96 1623.49 1526.58 1640.09 1532.99 1686.56 1534.29
 1699.84 1545.09 1716.43    1547 1729.71  1555.2 1756.27 1563.36 1823.94  1577.8
 1863.47 1581.64  2084.4  1574.7 2141.13 1578.77 2279.22 1598.64 2427.31 1602.56
#Mann= 5 ,-1 , 0
       0     .06       0  905.51     .08       0 1225.16     .05       0
 1384.49     .08       0 1550.46      .1       0
#XS Ineff= 2 , 0
          848.64 1544.64
Permanent Ineff=
       F       F
#Block Obstruct= 4 ,-1
     425  445.091569.141  524.29  554.221569.766  622.15  651.521571.219
  760.38  804.491570.213
Bank Sta=1225.16,1384.49
XS Rating Curve= 0 ,0
Exp/Cntr(USF)=0,0
Exp/Cntr=0.3,0.1

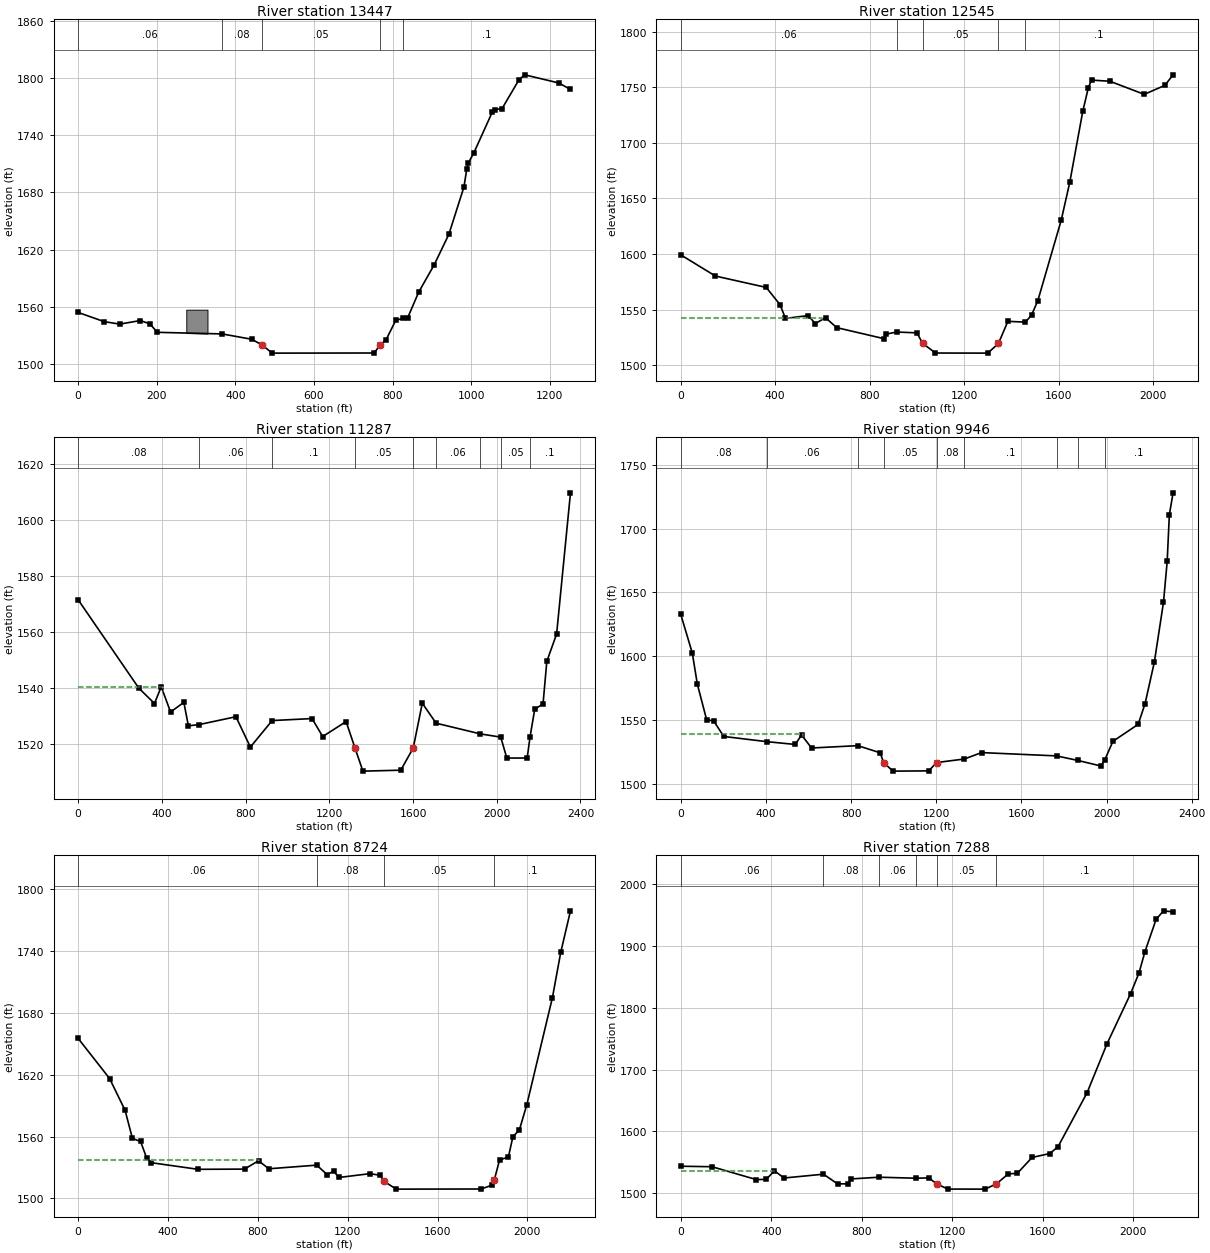
Type RM Length L Ch R = 1 ,13447   ,902.1,902.1,902.1
BEGIN DESCRIPTION:
ED
END DESCRIPTION:
Node Name=[ed]
XS GIS Cut Line= 2
 2063338.4335519263741.6376371612062195.61432082263229.259918177
#Sta/Elev= 30
       0 1554.08   65.87 1544.47  105.59 1541.82  157.97 1545.55  182.54 1542.14
  201.11 1533.22  366.25 1531.53  442.01  1525.9  467.18 1520.03  493.98 1511.38
  752.95 1511.52  768.41 1519.99  783.58 1525.61  808.13 1545.99  826.73 1547.77
  837.92 1548.18  866.28 1575.37  905.83 1604.16  943.07 1636.08  981.34 1685.64
  988.53 1704.34  992.12 1710.57  1006.5 1721.46 1053.24  1764.1 1060.44 1766.93
 1078.41 1768.02 1121.56 1798.32 1135.94 1803.43  1222.7  1794.9 1252.42 1788.09
#Mann= 5 ,-1 , 0
       0     .06       0  366.25     .08       0  467.18     .05       0
  768.41     .08       0  826.73      .1       0
#Block Obstruct= 1 ,-1
  275.08     3291556.971
Bank Sta=467.18,768.41
XS Rating Curve= 0 ,0
Exp/Cntr(USF)=0,0
Exp/Cntr=0.3,0.1

Type RM Length L Ch R = 1 ,12545   ,1258,1258,1258
Node Name=[ec]
XS GIS Cut Line= 3
2064197.55113707  263363.36072152063464.58608692262772.185252319
 2062353.2626148262504.202925326
#Sta/Elev= 30
       0 1599.28   146.7 1580.24   361.9    1570   420.2 1554.55   443.5 1542.13
   539.8 1544.72   569.5 1537.51     613 1542.78   660.5 1533.86   858.6 1524.04
   867.4 1527.93   913.8  1529.9  1000.3 1529.18    1024 1519.76 1078.69 1511.04
 1300.13 1510.95  1345.4 1519.67  1385.1 1539.52  1459.3 1538.82  1485.5 1545.11
  1512.2 1558.23  1611.2 1630.51  1647.3 1664.44  1702.3 1728.22  1726.1 1749.65
  1739.4 1756.34  1817.1 1755.31  1962.7 1743.53  2049.9  1751.6 2084.84 1761.08
#Mann= 5 ,-1 , 0
       0     .06       0   913.8     .08       0    1024     .05       0
  1345.4     .08       0  1459.3      .1       0
#XS Ineff= 2 , 0
          595.98 1542.83
Permanent Ineff=
       F       F
Bank Sta=1024,1345.4
XS Rating Curve= 0 ,0
Exp/Cntr=0.3,0.1

Type RM Length L Ch R = 1 ,11287   ,1341.1,1341.1,1341.1
Node Name=[eb]
XS GIS Cut Line= 3
2065048.81025991262023.4850797852064749.31224611262031.380837214
2062881.40347744261180.098319633
#Sta/Elev= 30
       0 1571.54   289.7 1540.04   364.7 1534.55   396.9 1540.53   441.5 1531.52
     505 1534.95   526.6  1526.6   577.1 1527.02   753.8 1529.84   822.9 1519.01
   926.9 1528.47  1117.6 1529.18  1168.4 1522.77  1280.2 1528.11  1322.6 1518.72
 1360.54 1510.44 1541.58 1510.77  1601.1 1518.72  1644.3 1534.65  1710.3 1527.53
    1922 1523.71  2019.2 1522.56  2048.2 1515.09  2145.5 1515.12  2158.9 1522.52
  2181.6 1532.56  2221.2 1534.37  2239.3 1549.58  2286.1 1559.33 2352.35 1609.67
#Mann= 9 ,-1 , 0
       0     .08       0   577.1     .06       0   926.9      .1       0
  1322.6     .05       0  1601.1     .08       0  1710.3     .06       0
    1922     .08       0  2019.2     .05       0  2158.9      .1       0
#XS Ineff= 2 , 0
          406.07 1540.26
Permanent Ineff=
       F       F
Bank Sta=1322.6,1601.1
XS Rating Curve= 0 ,0
Exp/Cntr=0.3,0.1

Type RM Length L Ch R = 1 ,9946    ,1222.1,1222.1,1222.1
Node Name=[ea]
XS GIS Cut Line= 2
2065419.30491956260604.8582325722063157.31089385260124.004566843
#Sta/Elev= 30
       0 1632.69    54.3 1602.24    77.8 1577.97   121.4 1550.05   154.9 1549.05
   201.9 1536.92   403.1 1532.86   537.3 1530.66   567.5 1538.03   614.4 1527.87
   831.7 1529.71   936.4 1524.12   953.2 1516.34  996.94 1509.72 1164.73 1509.92
  1201.4 1516.44  1332.2 1519.23  1412.7 1524.26  1764.9 1521.67  1865.5  1518.1
  1972.9 1513.76  1990.8 1518.21  2029.9 1533.12  2148.4 1546.42  2180.8 1562.59
  2224.4 1595.17  2267.4 1642.13  2284.8 1674.24    2295 1710.99 2312.54 1728.05
#Mann= 9 ,-1 , 0
       0     .08       0   403.1     .06       0   831.7     .08       0
   953.2     .05       0  1201.4     .08       0  1332.2      .1       0
  1764.9     .08       0  1865.5    .055       0  1990.8      .1       0
#XS Ineff= 2 , 0
          575.56 1538.46
Permanent Ineff=
       F       F
Bank Sta=953.2,1201.4
XS Rating Curve= 0 ,0
Exp/Cntr=0.3,0.1

Type RM Length L Ch R = 1 ,8724    ,1429,1436,1419
Node Name=[dz]
XS GIS Cut Line= 2
 2065624.2724679259241.3678982972063433.20851359259186.090806174
#Sta/Elev= 30
       0 1655.24     140 1616.32   208.9 1585.41   241.7 1558.08   277.8 1555.26
   305.5 1538.74   323.8 1534.63   533.8 1528.16   740.6 1528.36   802.9 1536.45
   848.9 1528.68  1062.2 1532.21  1108.2 1523.07  1137.7 1526.27  1160.7 1520.22
  1298.7 1523.93  1344.5  1522.4  1362.7 1516.38 1415.92 1508.92 1794.64 1509.04
  1843.3 1512.87  1852.1 1517.43  1876.1 1537.25  1915.5 1540.17  1935.2 1559.59
  1964.7 1566.68  1997.5    1591  2111.4 1694.91  2148.5 1738.93 2191.76 1779.14
#Mann= 4 ,-1 , 0
       0     .06       0  1062.2     .08       0  1362.7     .05       0
  1852.1      .1       0
#XS Ineff= 2 , 0
          804.23 1537.56
Permanent Ineff=
       F       F
Bank Sta=1362.7,1852.1
XS Rating Curve= 0 ,0
Exp/Cntr=0.3,0.1

Type RM Length L Ch R = 1 ,7288    ,1150,1150,1150
Node Name=[dy]
XS GIS Cut Line= 2
2065182.93864387257798.9944527172063007.64937301257775.245693376
#Sta/Elev= 30
       0 1543.77   138.3 1542.97   334.6 1522.11   377.8 1522.66   413.9 1536.32
   456.5 1524.75   630.4  1530.9   692.8 1515.28   738.7 1515.31   751.8 1523.25
   876.5 1526.03  1037.3 1524.41  1096.3 1524.94  1130.7 1515.21 1180.04 1506.86
 1344.62 1506.77  1394.9 1515.25  1447.4 1531.46  1486.8 1532.21  1552.4 1557.97
  1631.1  1564.3  1667.2 1575.46  1795.2 1662.43  1883.7 1741.86  1987.7  1822.7
  2024.9 1856.25  2051.1 1890.53  2100.3 1942.68  2133.1 1956.54 2175.42 1954.88
#Mann= 6 ,-1 , 0
       0     .06       0   630.4     .08       0   876.5     .06       0
  1037.3     .08       0  1130.7     .05       0  1394.9      .1       0
#XS Ineff= 2 , 0
          415.44 1536.32
Permanent Ineff=
       F       F
Bank Sta=1130.7,1394.9
XS Rating Curve= 0 ,0
Exp/Cntr=0.3,0.1

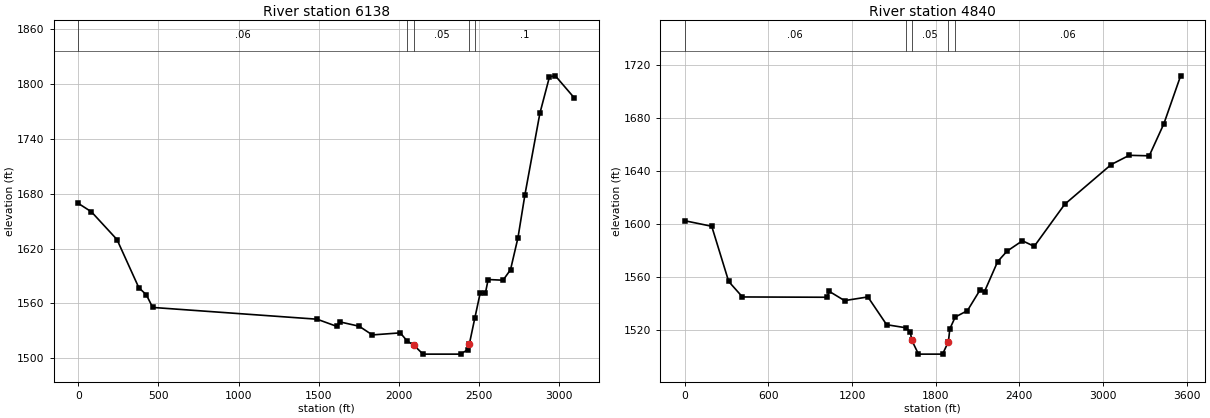
Type RM Length L Ch R = 1 ,6138    ,1298,1298,1298
Node Name=[dx]
XS GIS Cut Line= 4
2066306.18406703256512.1243751072065200.19895117256696.458847792
2064316.00412263256687.6616496882063244.12090606256498.467694721
#Sta/Elev= 30
       01669.371  81.5131660.203 241.1651629.836 377.5351577.139   424.11569.451
 464.0131555.5721490.0321542.694 1614.711534.7191634.3961539.6561752.5121535.002
1834.5371525.498  2008.8 1527.75  2052.1 1518.82  2092.1 1514.51 2150.85 1504.49
 2384.81 1504.49  2430.6 1509.45  2440.6 1516.09  2473.9 1543.81  2507.2 1571.01
  2540.5 1571.57  2557.2 1586.112650.1191585.354 2696.761596.7672743.4021631.917
2786.7121678.8732879.9961767.8782939.9641807.9142976.6111808.9423093.9321784.955
#Mann= 5 ,-1 , 0
       0     .06       0  2052.1     .08       0  2092.1     .05       0
  2440.6     .08       0  2473.9      .1       0
Bank Sta=2092.1,2440.6
XS Rating Curve= 0 ,0
Exp/Cntr(USF)=0,0
Exp/Cntr=0.3,0.1

Type RM Length L Ch R = 1 ,4840    ,4844,4840,4841
Node Name=[dw]
XS GIS Cut Line= 5
2066057.66834485255441.1829523392065314.81928966255392.652497423
2064545.53064541255414.7807781032063617.00552572255213.558218526
2062900.36296921256038.336357905
#Sta/Elev= 30
       01602.607 193.1911598.445  314.841556.873 413.4751545.2131017.9661544.993
1037.6591549.3371145.9711542.4591313.3631545.2311447.9321524.3121584.0631522.041
1617.6321519.0591627.7031512.724 1676.31 1502.16 1849.04 1502.16    1891  1511.5
  1901.1 1521.151939.9031530.0962027.1851534.8862119.8261550.8062150.0391549.292
2244.0341571.8072311.1741579.6792421.9551587.5362506.5971583.3252725.2041615.003
3058.8031644.9383187.9981651.8763331.686 1651.52 3436.731675.7053556.7461711.752
#Mann= 5 ,-1 , 0
       0     .06       01584.063     .08       01627.703     .05       0
    1891     .08       01939.903     .06       0
Bank Sta=1627.703,1891
XS Rating Curve= 0 ,0
Exp/Cntr(USF)=0,0
Exp/Cntr=0.3,0.1

Chan Stop Cuts=-1
Use User Specified Reach Order=0
Composite Channel Slope=5